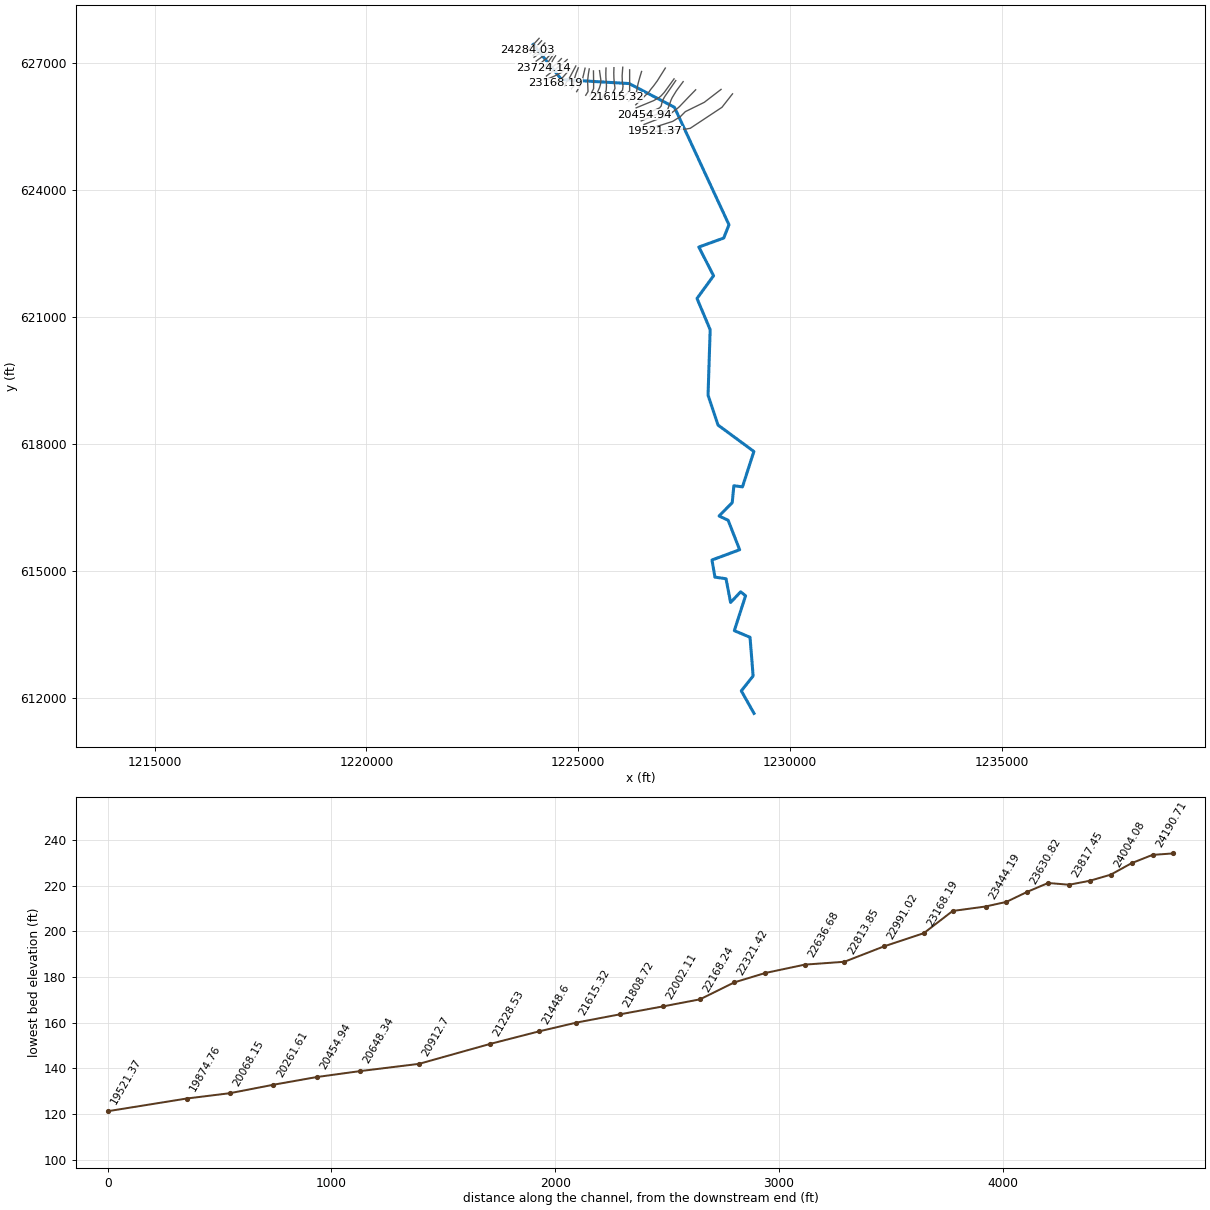
--- 264_ras.prj (project) ---

Proj Title=264
Current Plan=p01
Default Exp/Contr=0.3,0.1
English Units
Geom File=g01
Flow File=f01
Plan File=p01
Y Axis Title=Elevation
X Axis Title(PF)=Main Channel Distance
X Axis Title(XS)=Station
BEGIN DESCRIPTION:
RFD model 264 exported to HEC-RAS
END DESCRIPTION:

--- 264_ras.p01 (plan) ---

Plan Title=Plan 01
Program Version=4.10
Short Identifier=Plan 01
Geom File=g01
Flow File=f01
Subcritical Flow
Calc Critical at every XS
Secant Critical Depth

--- 264_ras.f01 (steady flow) ---

Flow Title=Flow 01
Program Version=5.01
Number of Profiles= 5
Profile Names=10yr,25yr,50yr,100yr,500yr
River Rch & RM=264,77,24284.03
  503.04  503.04  503.04  833.68 1029.06
River Rch & RM=264,77,24190.71
   513.4   513.4   513.4  856.52 1061.35
River Rch & RM=264,77, 24097.4
  516.21  516.21  516.21  862.77  1070.2
River Rch & RM=264,77,24004.08
  523.98  523.98  523.98  880.05 1094.73
River Rch & RM=264,77,23817.45
  532.65  532.65  532.65  899.43 1122.33
River Rch & RM=264,77,23724.14
  536.91  536.91  536.91  908.98 1135.95
River Rch & RM=264,77,23630.82
  538.49  538.49  538.49  912.53 1141.04
River Rch & RM=264,77,23537.51
  541.63  541.63  541.63  919.61 1151.16
River Rch & RM=264,77,23444.19
  548.35  548.35  548.35  934.78 1172.88
River Rch & RM=264,77, 23297.4
  554.44  554.44  554.44  948.58 1192.69
River Rch & RM=264,77,23168.19
  558.94  558.94  558.94  958.81 1207.41
River Rch & RM=264,77,22991.02
  560.43  560.43  560.43   962.2 1212.29
River Rch & RM=264,77,22813.85
  656.75  656.75  656.75 1187.65 1542.04
River Rch & RM=264,77,22636.68
  657.53  657.53  657.53 1189.51 1544.81
River Rch & RM=264,77,22459.51
   678.7   678.7   678.7 1240.61 1620.89
River Rch & RM=264,77,22321.42
  687.11  687.11  687.11 1261.05 1651.45
River Rch & RM=264,77,22168.24
  693.94  693.94  693.94 1277.72 1676.41
River Rch & RM=264,77,22002.11
  697.49  697.49  697.49 1286.41 1689.45
River Rch & RM=264,77,21808.72
  707.29  707.29  707.29 1310.46 1725.61
River Rch & RM=264,77,21615.32
  714.85  714.85  714.85 1329.09 1753.66
River Rch & RM=264,77, 21448.6
  717.23  717.23  717.23 1334.96 1762.53
River Rch & RM=264,77,21228.53
  743.29  743.29  743.29 1399.72 1860.58
River Rch & RM=264,77, 20912.7
  795.08  795.08  795.08 1530.59 2060.71
River Rch & RM=264,77,20648.34
  801.41  801.41  801.41 1546.79 2085.66
River Rch & RM=264,77,20454.94
  802.84  802.84  802.84 1550.45  2091.3
River Rch & RM=264,77,20261.61
  810.76  810.76  810.76 1570.81 2122.71
River Rch & RM=264,77,20068.15
  878.33  878.33  878.33 1746.88 2396.75
River Rch & RM=264,77,19874.76
  884.02  884.02  884.02 1761.91 2420.34
River Rch & RM=264,77,19521.37
  888.19  888.19  888.19 1772.95 2437.68
River Rch & RM=264,77,19352.23
  917.96  917.96  917.96 1852.26 2562.71
River Rch & RM=264,77,19167.16
  920.28  920.28  920.28 1858.47 2572.54
River Rch & RM=264,77,18707.09
  974.93  974.93  974.93 2006.35 2807.79
River Rch & RM=264,77,18515.03
  979.36  979.36  979.36 2018.47 2827.18
River Rch & RM=264,77,18122.54
  985.01  985.01  985.01 2033.95 2851.98
River Rch & RM=264,77,17730.05
 1037.68 1037.68 1037.68 2179.53 3086.45
River Rch & RM=264,77,17337.55
 1042.09 1042.09 1042.09 2191.84 3106.39
River Rch & RM=264,77,16945.06
 1045.71 1045.71 1045.71 2201.96 3122.79
River Rch & RM=264,77,16552.57
 1339.14 1339.14 1339.14 3057.54 4544.48
River Rch & RM=264,77,15767.58
 1714.52 1714.52 1714.52 4244.35 6611.24
River Rch & RM=264,77,15589.06
 1730.99 1730.99 1730.99 4298.53 6707.77
River Rch & RM=264,77,15053.49
 1731.69 1731.69 1731.69 4300.84 6711.91
River Rch & RM=264,77,14591.93
 1739.04 1739.04 1739.04  4325.1 6755.18
River Rch & RM=264,77,14042.14
 1777.81 1777.81 1777.81 4453.53 6984.93
River Rch & RM=264,77,13774.08
 1779.16 1779.16 1779.16 4458.01 6992.97
River Rch & RM=264,77,13482.19
 1782.02 1782.02 1782.02 4467.53 7010.03
River Rch & RM=264,77,13096.84
 1799.04 1799.04 1799.04 4524.25 7111.84
River Rch & RM=264,77,12745.67
 1805.15 1805.15 1805.15 4544.66 7148.53
River Rch & RM=264,77,12284.11
 1809.59 1809.59 1809.59  4559.5 7175.22
River Rch & RM=264,77,11822.55
 1898.01 1898.01 1898.01 4857.55 7713.76
River Rch & RM=264,77,11360.98
 1905.47 1905.47 1905.47 4882.89 7759.76
River Rch & RM=264,77,11225.02
 1910.69 1910.69 1910.69 4900.66 7792.04
River Rch & RM=264,77,11096.98
 1928.98 1928.98 1928.98 4963.03 7905.48
River Rch & RM=264,77,10599.71
 1932.85 1932.85 1932.85 4976.23 7929.52
River Rch & RM=264,77,10102.44
  1973.8  1973.8  1973.8 5116.66 8185.79
River Rch & RM=264,77,9392.273
 1983.61 1983.61 1983.61 5150.42 8247.56
River Rch & RM=264,77,8956.277
 1992.06 1992.06 1992.06 5179.59 8300.96
River Rch & RM=264,77,8699.919
 1992.77 1992.77 1992.77 5182.03 8305.44
River Rch & RM=264,77,8113.351
 2000.26 2000.26 2000.26 5207.88  8352.8
River Rch & RM=264,77,7616.078
 2008.89 2008.89 2008.89 5237.72 8407.53
River Rch & RM=264,77,7118.806
 2015.03 2015.03 2015.03 5258.98 8446.54
River Rch & RM=264,77,6621.534
 2019.82 2019.82 2019.82 5275.59 8477.04
River Rch & RM=264,77,6124.261
 2023.35 2023.35 2023.35 5287.84 8499.54
River Rch & RM=264,77, 5410.51
 2033.82 2033.82 2033.82 5324.19 8566.36
River Rch & RM=264,77,5129.717
 2037.39 2037.39 2037.39 5336.58 8589.14
River Rch & RM=264,77,4553.432
 2042.24 2042.24 2042.24 5353.45 8620.18
River Rch & RM=264,77,3347.141
 2047.95 2047.95 2047.95 5373.34  8656.8
River Rch & RM=264,77,2969.726
 2049.58 2049.58 2049.58 5379.01 8667.25
River Rch & RM=264,77,2056.195
 2052.63 2052.63 2052.63 5389.63 8686.81
River Rch & RM=264,77,1672.005
 2054.05 2054.05 2054.05 5394.58 8695.93
River Rch & RM=264,77,1339.308
 2057.22 2057.22 2057.22 5405.65 8716.31
Boundary for River Rch & Prof#=264,77,1
Up Type= 0
Dn Type= 2
Boundary for River Rch & Prof#=264,77,2
Up Type= 0
Dn Type= 2
Boundary for River Rch & Prof#=264,77,2
Up Type= 0
Dn Type= 2
Boundary for River Rch & Prof#=264,77,2
Up Type= 0
Dn Type= 2
Boundary for River Rch & Prof#=264,77,2
Up Type= 0
Dn Type= 2

--- 264_ras.g01 (geometry) ---

Geom Title=264
Program Version=4.10

River Reach=264,77
Reach XY= 30
1223938.01085951627432.536778772 1224607.1773047626604.203671905
1226203.01016448626510.0369869281227271.58295077625950.450514835
1228558.80272082623177.0183539391228434.85616305622863.809765488
1227847.64785069622651.2299016421228195.46945971621972.852055327
1227804.07967487621438.1254472321228114.91289507620700.625657158
1228064.91286487619153.1261180681228300.74610817618448.959653637
1229146.57917381617826.459813914 1228877.4125623 616990.62673657
1228674.07928973617016.4600681131228635.74595613616618.126854185
1228324.91270538616303.1269567151228539.07930591616202.293647099
 1228810.7458722615506.4605125211228157.41272466615264.793936557
1228227.41269223614859.794054778 1228489.0792806614822.294058326
1228597.27367683614262.016443764 1228834.0791698614513.405251158
1228950.74579933 614420.349719831228684.77363169613596.738860996
1229055.60685106613441.1833408841229128.91394536 612527.65990442
1228849.74735089612175.9933502571229149.71222833 611644.38649406

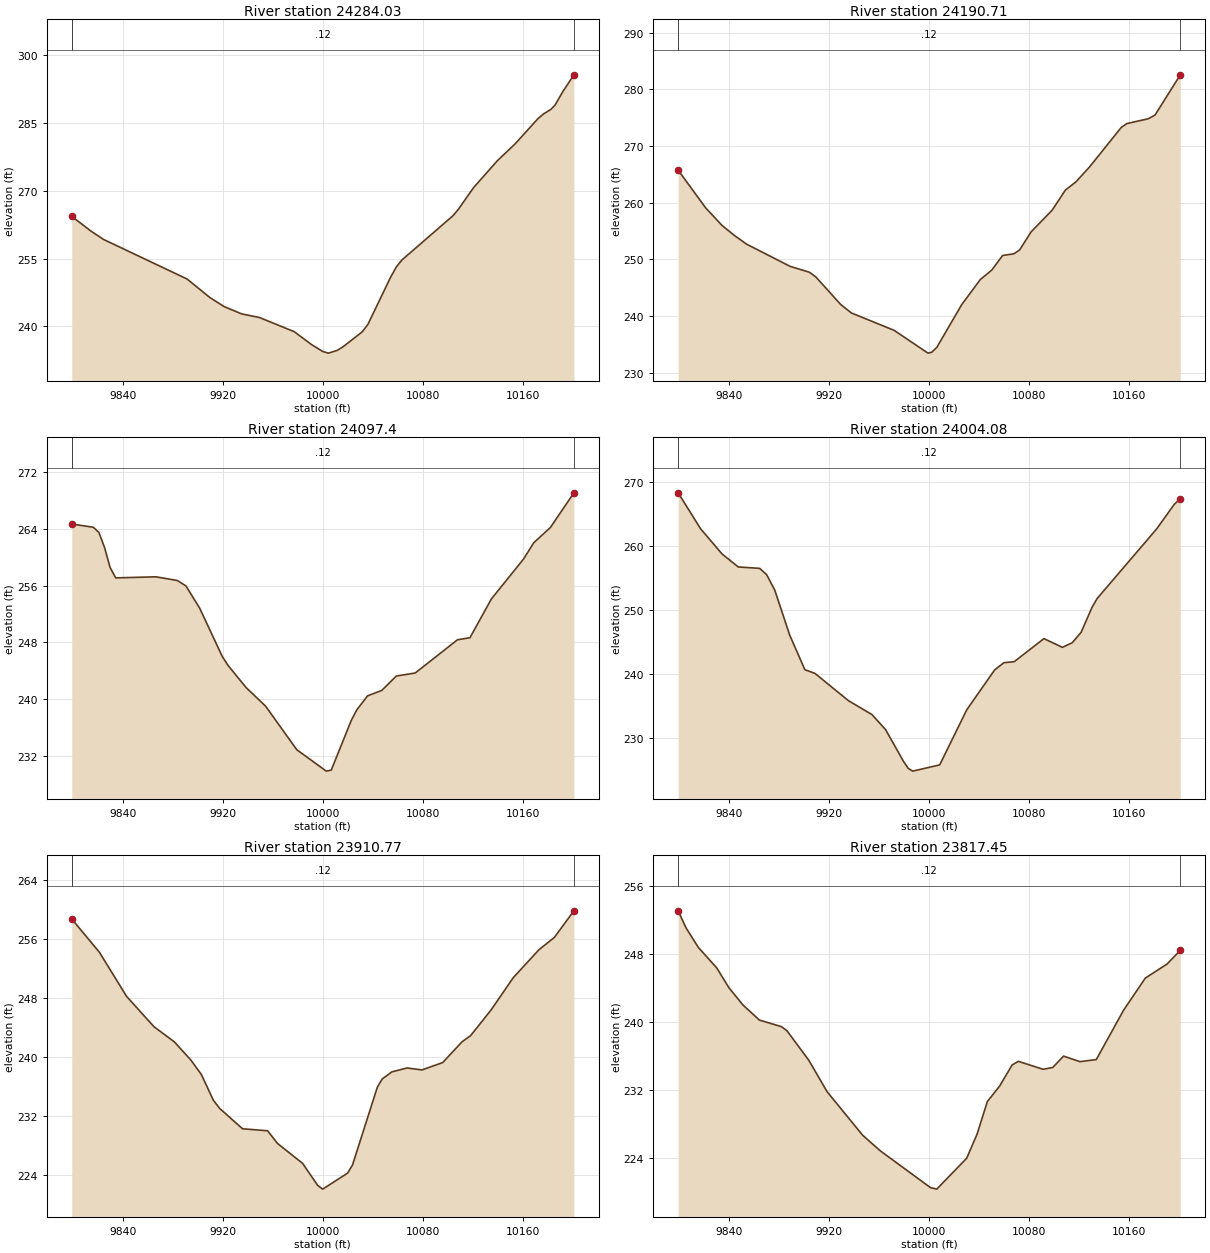
Type RM Length L Ch R = 1 ,24284.03,93.315100,93.315100,93.315100
XS GIS Cut Line= 6
1224077.23575672627577.3437160831224013.22827117627507.301127083
 1223965.9189442627458.0818263161223939.42410409 627432.48443634
1223937.95851707627431.1235341821223793.31769089627293.000736928
#Sta/Elev= 30
9799.007264.34249814.608261.04239824.625259.22069891.291250.49879909.431246.4297
9920.869244.41179935.072242.78149949.275241.98339977.116238.85199990.802236.0222
9999.908234.474210004.43234.106410011.43234.695910016.18 235.50710031.65238.8399
10036.19240.514710054.33250.935210058.94253.2019 10063.4254.724210104.23264.4983
10108.77 266.00810120.69270.7027 10139.7276.648110153.95280.377110172.28285.9684
10176.82287.032310182.45287.979910185.89 288.94510191.95291.8463   10201295.6447
#Mann= 3 , 0 , 0
9799.007    0.12       09799.007    0.12       0   10201    0.12       0
#XS Ineff= 2 , 0
       0                               0
Bank Sta=9799.007,10201
Exp/Cntr=0.3,0.1

Type RM Length L Ch R = 1 ,24190.71,93.315000,93.315000,93.315000
XS GIS Cut Line= 6
1224135.68506323627519.1569106981224079.23715818627455.054312014
 1224012.8102822627375.1500956741223965.31615577627321.030495438
1223918.07850648627272.3333712351223864.90547986627222.599331108
#Sta/Elev= 30
9799.005265.72949820.988259.08839834.103255.9813  9843.8254.24889853.729252.6843
9888.617248.76399904.013247.73279909.145246.91459929.175242.03129937.708 240.541
 9971.84237.4874    9999233.464510002.01 233.62610006.09234.492810025.99242.0181
10040.91246.451210050.03248.104410058.76250.689610067.83250.9782 10072.4251.6765
10081.54254.842610098.48258.698210108.96262.209610117.32263.646410128.18266.2544
10153.77273.277910158.26 273.94510175.23274.785810180.72275.436710200.98282.5383
#Mann= 3 , 0 , 0
9799.005    0.12       09799.005    0.12       010200.98    0.12       0
#XS Ineff= 2 , 0
       0                               0
Bank Sta=9799.005,10200.98
Exp/Cntr=0.3,0.1

Type RM Length L Ch R = 1 , 24097.4,93.315100,93.315100,93.315100
XS GIS Cut Line= 6
1224214.31373255627466.0622225871224118.11632123627362.814138853
1224071.49227323627298.1813478681224054.74263767627278.748213632
 1224017.6680531627244.4307749671223937.47784113627176.825041056
#Sta/Elev= 30
9799.029 264.7079816.272264.25759820.756263.5204 9825.24261.41529829.725258.5759
9834.209257.11089866.357257.26359883.535256.74299890.421255.97459901.471252.8227
9919.408246.05189924.111244.7619 9938.55241.64329954.277238.99569979.082232.8783
10002.76229.847210006.72229.987210022.83237.031210027.22238.504810035.82240.4717
10047.13241.228410058.85243.268210073.95243.691710107.74248.377110117.75248.6686
10134.92254.142410160.67259.777210168.82262.069510182.12264.215610200.96269.1126
#Mann= 3 , 0 , 0
9799.029    0.12       09799.029    0.12       010200.96    0.12       0
#XS Ineff= 2 , 0
       0                               0
Bank Sta=9799.029,10200.96
Exp/Cntr=0.3,0.1

Type RM Length L Ch R = 1 ,24004.08,93.315000,93.315000,93.315000
XS GIS Cut Line= 6
1224293.63079044627347.9529832791224244.90212511627306.484800558
1224203.57104842627277.1813634061224067.57177746 627208.34483772
1224015.93104223627174.2386701411223957.83041025627130.341549514
#Sta/Elev= 30
9799.058268.30389817.002262.68459834.234258.73549847.159256.71769864.301256.4975
9869.885255.50569876.366253.09899888.432246.00669900.497 240.6529908.541240.0794
9935.298235.82259954.186  233.649965.049231.29049979.514226.29179983.131225.2448
9986.747224.801610008.38225.776310030.03234.383710052.35240.617810059.79241.7576
   10068241.905410091.81245.5157 10106.6244.148810114.47 244.87510121.58246.4971
10130.29250.4031 10134.4251.786910182.01262.660910196.08266.487710200.96267.4101
#Mann= 3 , 0 , 0
9799.058    0.12       09799.058    0.12       010200.96    0.12       0
#XS Ineff= 2 , 0
       0                               0
Bank Sta=9799.058,10200.96
Exp/Cntr=0.3,0.1

Type RM Length L Ch R = 1 ,23910.77,93.315100,93.315100,93.315100
XS GIS Cut Line= 6
1224328.81247284627281.3466681911224284.30767661627240.743636915
1224237.01749555627202.5872220891224170.79137436627156.007387523
1224084.54887633627097.0243967131224008.26469231627039.564878106
#Sta/Elev= 30
9799.026258.72089821.145254.22099842.942248.23349864.849244.13179881.047242.0941
9894.358239.61949902.789237.65429912.395234.1635 9917.62233.03499935.716230.3044
9955.773230.03599963.796228.30489983.853 225.6159995.888222.63769999.896222.1294
10019.78224.291510023.75225.390910043.62235.9297 10047.6237.060310055.28238.0115
10067.47238.5434 10079.4 238.27710095.97239.276310111.39242.079210118.37242.9354
10134.73246.409410152.46250.7778   10173254.558910185.32256.224810200.99259.8301
#Mann= 3 , 0 , 0
9799.026    0.12       09799.026    0.12       010200.99    0.12       0
#XS Ineff= 2 , 0
       0                               0
Bank Sta=9799.026,10200.99
Exp/Cntr=0.3,0.1

Type RM Length L Ch R = 1 ,23817.45,93.315000,93.315000,93.315000
XS GIS Cut Line= 6
1224372.76239569627229.5241085561224259.55332316627105.968777452
1224244.16059744627093.3774398741224219.69496624627078.480853657
1224194.60989699627059.6142853621224078.41995993626957.946967046
#Sta/Elev= 30
 9799.04253.08469805.347 251.0799815.167248.78929829.897246.37879839.717244.0366
9850.848242.02719864.078 240.2469881.717239.47259886.127238.98929903.546235.5363
9918.276231.82169946.738226.70639960.881224.873810001.06220.549610006.02220.3789
10029.99224.010110038.31226.847210046.52230.671210056.35232.488710066.31234.9598
 10071.3235.396110091.22234.461810098.83234.673610107.55236.010910120.62235.3605
 10133.7235.6007 10155.5241.389510172.94245.175910190.38246.832110200.97 248.441
#Mann= 3 , 0 , 0
 9799.04    0.12       0 9799.04    0.12       010200.97    0.12       0
#XS Ineff= 2 , 0
       0                               0
Bank Sta=9799.04,10200.97
Exp/Cntr=0.3,0.1

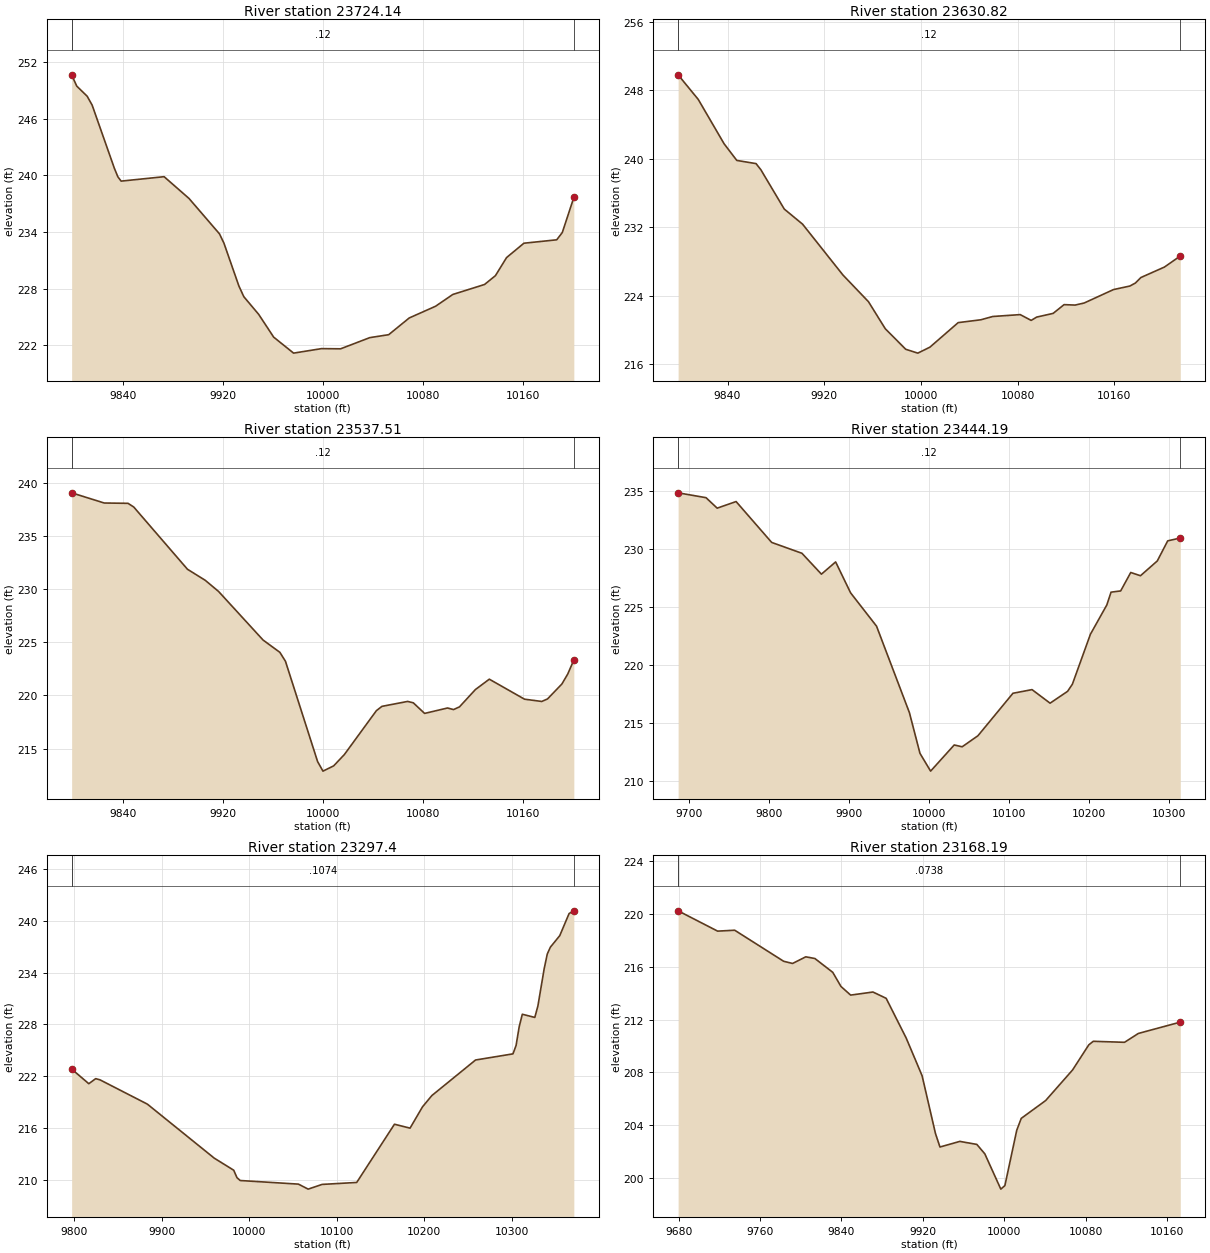
Type RM Length L Ch R = 1 ,23724.14,93.315100,93.315100,93.315100
XS GIS Cut Line= 6
1224418.71509105627197.4986955441224374.73022465627139.482679594
1224310.55242578627046.5000963951224257.56938856626975.005314896
1224219.85075686626928.6982177561224174.13207371626879.076920235
#Sta/Elev= 30
9799.011250.66639803.075249.47419811.452248.39449815.426247.45179833.174240.7691
9836.012239.85179838.605239.39629873.026239.86659892.959237.55759917.353233.8035
9920.864232.83499932.823228.2985 9936.81227.14469948.769225.26189960.728222.8547
9976.674221.1599    9999221.636910014.32221.617610037.67222.803110052.77223.1142
10069.25  224.8910090.27226.127610104.13227.381410129.52228.437710138.22229.3732
10147.14231.2907   10161232.812310187.29233.174710191.76233.951210200.98237.6652
#Mann= 3 , 0 , 0
9799.011    0.12       09799.011    0.12       010200.98    0.12       0
#XS Ineff= 2 , 0
       0                10042.09       0
Bank Sta=9799.011,10200.98
Exp/Cntr=0.3,0.1

Type RM Length L Ch R = 1 ,23630.82,93.315000,93.315000,93.315000
XS GIS Cut Line= 6
 1224465.5981258 627165.338238431224422.06729285627102.176835903
 1224391.4744735627046.0262659451224379.11150255627011.837965931
1224369.14503848626957.4862825441224236.71508747626830.869584501
#Sta/Elev= 30
9799.099249.80459815.773246.92729837.147241.74449847.649239.79739863.588239.4251
9867.572238.70759886.934234.11139902.107232.34219935.457226.40619956.595223.2836
 9970.55220.11259987.449217.71859997.435217.268810007.44217.965210030.84220.8346
10049.59221.166910059.47221.552410082.16221.772310091.24221.094810095.78221.4806
 10109.4 221.91510118.47222.938210127.55222.885910135.05223.126510159.33224.6976
10172.94225.113710177.48225.464110182.02226.107910201.51227.331210214.63228.6248
#Mann= 3 , 0 , 0
9799.099    0.12       09799.099    0.12       010214.63    0.12       0
#XS Ineff= 2 , 0
       0                10051.69       0
Bank Sta=9799.099,10214.63
Exp/Cntr=0.3,0.1

Type RM Length L Ch R = 1 ,23537.51,93.315100,93.315100,93.315100
XS GIS Cut Line= 6
1224603.07899482627099.0206477551224512.97087051627004.409238894
1224483.80132673 626977.15312564 1224425.5795757626928.394139271
1224354.34908715626853.0940849431224317.42894439626816.822838156
#Sta/Elev= 30
9799.021239.08879825.115238.12919844.144238.09969848.727237.75099891.715231.8884
9905.987230.84419916.688229.78799952.218225.22149965.689 224.0599970.153223.2173
9995.877213.767210000.17212.869710008.72213.364910017.27214.428210042.91218.5646
10047.37218.971710067.96219.436910072.47219.304810081.51 218.30710099.89218.8177
10104.66218.666610109.43218.924310122.15220.552710133.31221.531410161.48219.6475
10175.28219.432910179.88219.671410191.38221.076310196.07222.016510200.95 223.338
#Mann= 3 , 0 , 0
9799.021    0.12       09799.021    0.12       010200.95    0.12       0
#XS Ineff= 2 , 0
       0                               0
Bank Sta=9799.021,10200.95
Exp/Cntr=0.3,0.1

Type RM Length L Ch R = 1 ,23444.19,146.792300,146.792300,146.792300
XS GIS Cut Line= 6
1224741.39140082 627077.799456921224630.34806899626974.823797707
1224524.45189991626897.9738434061224469.91709053626849.581380481
1224342.34032738626760.2475419351224251.25780579626687.480334825
#Sta/Elev= 30
9686.187234.81159721.056234.39349734.999233.49159758.646234.05949803.112230.5403
 9840.96229.60339865.282227.80659883.062228.86019901.766226.19729934.195223.3256
 9975.26215.87949988.462212.373510001.76210.841810031.25213.0945 10041.2212.9387
10060.95213.891310104.67217.547610128.52217.861410151.09216.694310172.94217.7141
10178.94218.3257 10201.5222.632410222.02225.158610227.27226.255510239.29 226.361
10251.89227.950510264.07 227.67110285.09228.946410298.08230.674210313.83230.9205
#Mann= 3 , 0 , 0
9686.187    0.12       09686.187    0.12       010313.83    0.12       0
#XS Ineff= 2 , 0
       0                               0
Bank Sta=9686.187,10313.83
Exp/Cntr=0.3,0.1

Type RM Length L Ch R = 1 , 23297.4,129.207700,129.207700,129.207700
XS GIS Cut Line= 4
1224707.77038767626868.3863283321224601.52195885626770.637773789
1224431.52447267 626682.451577821224212.65270921626590.015444733
#Sta/Elev= 30
9797.284222.81619816.879221.12169824.776221.70719829.622221.5706 9883.75218.7519
9960.176212.48469982.352211.08859986.048210.22979989.744209.894210056.27209.4761
10067.36208.8956 10083.3209.4424 10122.8209.669510165.92216.421210183.72 215.967
10197.97218.442410208.65219.747910258.51223.868210301.25224.580110304.81225.5593
10308.37227.735710311.93229.173610326.18228.806910329.74230.144710336.86234.4354
10340.42 236.15810343.99236.955810354.67238.286410365.35240.852510370.76241.1668
#Mann= 3 , 0 , 0
9797.284  0.1074       09797.284  0.1074       010370.76  0.1074       0
#XS Ineff= 2 , 0
       0                10054.93       0
Bank Sta=9797.284,10370.76
Exp/Cntr=0.3,0.1

Type RM Length L Ch R = 1 ,23168.19,177.171100,177.171100,177.171100
XS GIS Cut Line= 6
1224811.29302021626856.4653257171224639.87935688626660.622385269
1224616.08181481626639.8002462581224550.83061136626594.686221817
1224510.29277262626560.493462299 1224460.2238599626512.430895006
#Sta/Elev= 30
9679.428220.2333 9718.27218.69499735.058218.76369783.162216.41199791.944216.2456
9804.952216.74919813.898216.62019831.461215.57269839.508214.50519849.025213.8486
9870.979214.08159883.937213.60639903.683210.58769919.278207.74039932.451203.3539
9936.842  202.349956.385202.76599973.092 202.5379980.949201.82159996.663199.1495
10000.67199.419310012.32203.610810016.75204.510110040.73205.859510067.21208.1773
10083.12210.076610087.56210.348710118.27210.272310131.92210.944910173.11211.8021
#Mann= 3 , 0 , 0
9679.428  0.0738       09679.428  0.0738       010173.11  0.0738       0
#XS Ineff= 2 , 0
       0                               0
Bank Sta=9679.428,10173.11
Exp/Cntr=0.3,0.1

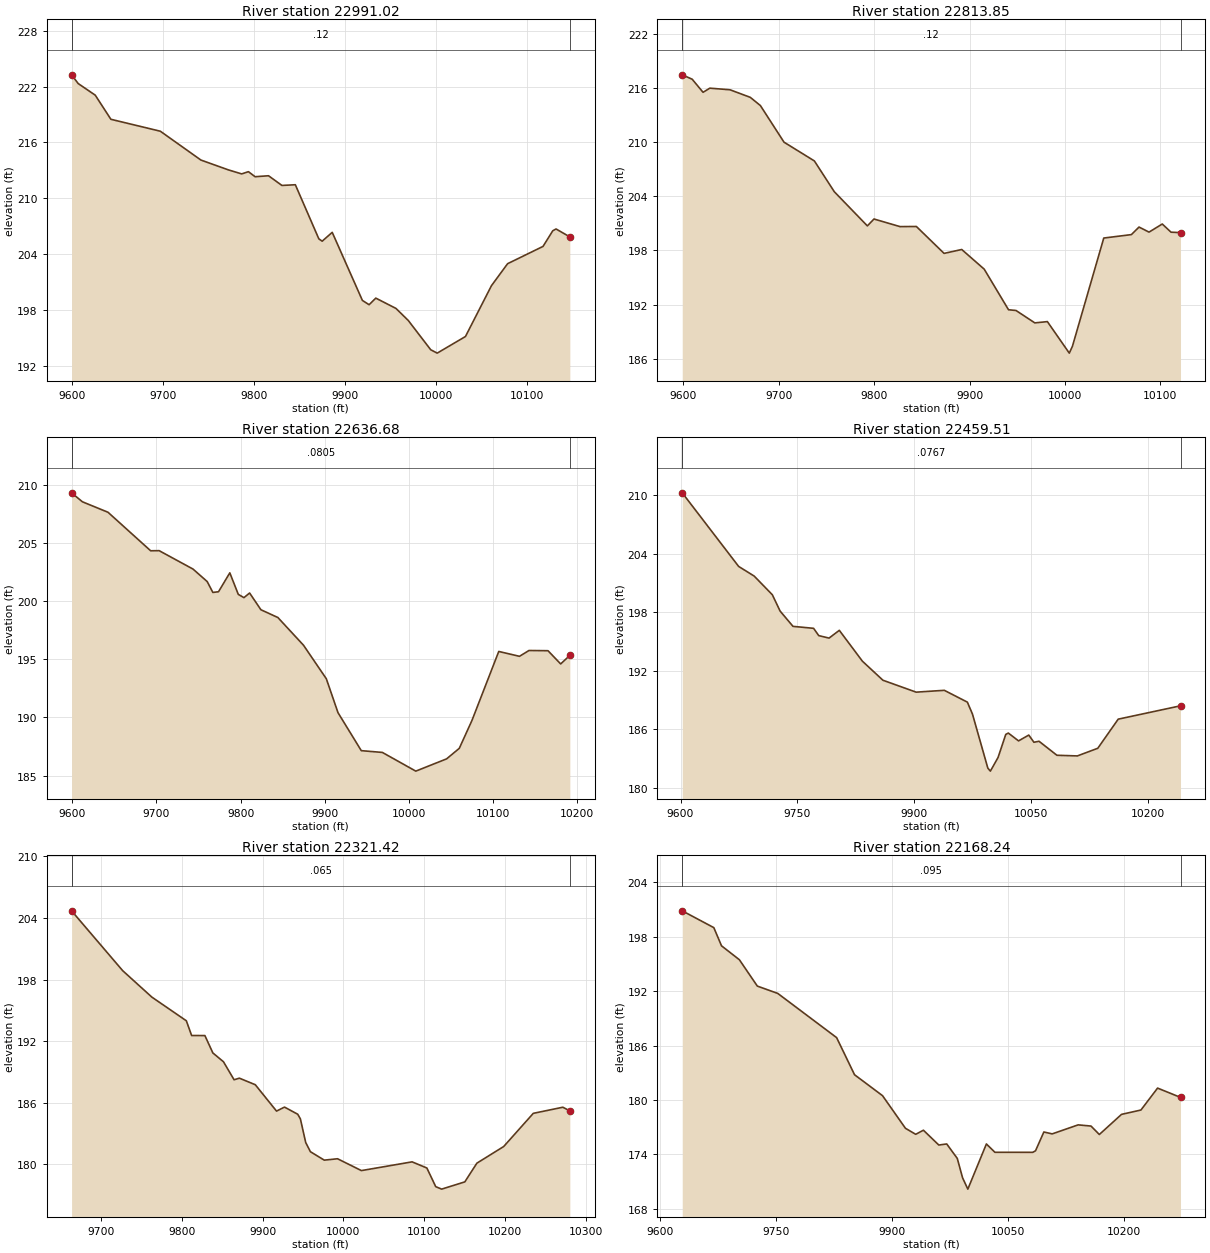
Type RM Length L Ch R = 1 ,22991.02,177.171100,177.171100,177.171100
XS GIS Cut Line= 6
1224943.86454328626925.0621558781224776.79389918626610.794335745
1224761.61408127626588.7186097381224736.23155779626569.302000532
1224724.44424446626552.7316155111224681.16044587626448.812597744
#Sta/Elev= 30
9599.083223.25989606.381222.32119625.113221.07699642.285 218.4899696.655217.2089
9741.247214.11559771.413213.06199786.093212.62779793.464212.86879800.835212.3266
9815.577212.42969830.319211.39039845.062211.46559870.861205.66449874.546205.4085
9885.603206.35739918.773199.05149926.144198.59239933.515199.30019955.676198.1946
9969.134196.90879993.878193.7592   10001193.397610032.05195.179310060.65 200.636
10078.37202.992110117.35204.850510128.03206.526510131.63  206.72 10146.8  205.87
#Mann= 3 , 0 , 0
9599.083    0.12       09599.083    0.12       0 10146.8    0.12       0
#XS Ineff= 2 , 0
       0                               0
Bank Sta=9599.083,10146.8
Exp/Cntr=0.3,0.1

Type RM Length L Ch R = 1 ,22813.85,177.171000,177.171000,177.171000
XS GIS Cut Line= 6
1225002.33322519626879.8806990531224949.43458137626747.549256921
1224910.32184348626621.7456566991224895.23080936626546.657277688
1224892.40872306 626444.089333461224843.81688827626395.974544525
#Sta/Elev= 30
9599.057217.43029609.471216.94489620.881215.49619627.948215.95459649.147215.7753
9670.347 214.9399680.947214.02769705.679209.97979737.479207.9044 9758.35204.5004
9793.005200.71829799.936 201.4799827.231200.63869844.337200.65369873.353197.6766
9891.863198.10769915.395195.93289940.869191.44049948.678191.36169968.436189.9885
9981.575190.130310004.54186.643210007.82187.401310040.65 199.37410069.61 199.755
10077.58200.589510088.08  200.0310101.93200.926810111.16200.019910121.03199.9782
#Mann= 3 , 0 , 0
9599.057    0.12       09599.057    0.12       010121.03    0.12       0
#XS Ineff= 2 , 0
       0                               0
Bank Sta=9599.057,10121.03
Exp/Cntr=0.3,0.1

Type RM Length L Ch R = 1 ,22636.68,177.171100,177.171100,177.171100
XS GIS Cut Line= 6
1225162.04827365626872.0723561061225106.80621146626636.296562346
1225092.43995897626579.6121545141225076.01418023626531.328842103
1225044.82848305626462.7447021811224963.48599324626318.627440095
#Sta/Elev= 30
9599.052209.30329611.899208.53399642.352207.63369693.098204.32319703.183204.3339
9743.522 202.749 9760.33201.67829767.053200.74489773.776200.80339787.222202.4282
9797.307200.5763 9804.03200.29729810.753200.69629824.199199.2573 9844.39198.5883
9874.851 196.2089901.981193.32879915.843190.41749943.567187.14889968.626186.9968
10008.37185.389910045.03186.4438 10060.1187.348410075.17189.745410107.04195.6727
10131.68195.255510142.98195.754710165.59 195.73610180.66194.600310191.56195.3345
#Mann= 3 , 0 , 0
9599.052  0.0805       09599.052  0.0805       010191.56  0.0805       0
#XS Ineff= 2 , 0
       0                               0
Bank Sta=9599.052,10191.56
Exp/Cntr=0.3,0.1

Type RM Length L Ch R = 1 ,22459.51,138.087500,138.087500,138.087500
XS GIS Cut Line= 6
1225260.91292739626855.559701905 1225239.9365344626733.004866764
1225225.31324375 626601.225823731225223.26461008626533.164616376
1225231.73889217626320.2289927011225178.01475453626233.983439043
#Sta/Elev= 30
9602.195210.23389674.637202.68969694.608201.69889717.908199.78629727.885198.1145
9744.425196.54679770.889 196.3459777.505195.59769790.737195.34339803.931196.1384
9833.584192.97539859.939191.02369902.609189.80249938.739189.99119968.342  188.78
 9974.92187.55689994.656182.01539997.945181.7076 10007.8183.111410017.66185.4689
10020.95185.6108 10034.1184.806410047.25 185.40410053.82184.6659 10060.4184.7686
10083.36183.332510109.61183.265810135.85184.049210162.09187.034310242.08188.4021
#Mann= 3 , 0 , 0
9602.195  0.0767       09602.195  0.0767       010242.08  0.0767       0
#XS Ineff= 2 , 0
       0                10089.48       0
Bank Sta=9602.195,10242.08
Exp/Cntr=0.3,0.1

Type RM Length L Ch R = 1 ,22321.42,153.184500,153.184500,153.184500
XS GIS Cut Line= 4
1225360.26394174626807.9652172631225364.51387885626512.594585031
1225363.35592929626390.1370272041225275.79316956626212.092749089
#Sta/Elev= 30
9663.816204.69599727.002198.87159763.094196.2972 9805.75193.99159812.312 192.558
9828.718192.55139838.561190.86159851.686190.00029864.811188.24919871.373188.4042
 9891.06187.7652 9917.31185.19879927.153 185.5889943.559184.8913 9946.84184.4362
9953.402182.13879959.217181.2449 9976.37180.42269992.775180.5587 10022.3179.4058
10084.98180.256810103.26179.658910114.23177.841210121.54177.601910150.21 178.308
10165.08180.127110198.32181.752310234.88184.979410271.44185.574610280.09185.2196
#Mann= 3 , 0 , 0
9663.816   0.065       09663.816   0.065       010280.09   0.065       0
#XS Ineff= 2 , 0
       0                10055.03       0
Bank Sta=9663.816,10280.09
Exp/Cntr=0.3,0.1

Type RM Length L Ch R = 1 ,22168.24,166.124000,166.124000,166.124000
XS GIS Cut Line= 6
 1225503.4563449626814.8164118831225535.74285227626583.860997781
1225531.84052354626531.2124245611225524.40712458626485.701077282
1225500.82916254626406.3112939751225407.13730916626196.039576471
#Sta/Elev= 30
 9628.61200.84949669.507 198.9979679.445196.99639702.635195.45689725.824192.5551
9752.326191.74649828.519186.87479851.708182.78539887.966180.47719917.605176.8872
9930.903176.21959940.875176.67249960.824175.03829971.072175.15869984.736173.5635
9991.567171.43219998.399170.179210022.42175.155810033.48174.239110082.45 174.234
10086.04174.404810096.82176.4748 10107.6176.267210141.24177.260410157.88177.1297
10168.66176.199510197.39178.417410222.53 178.89710244.08181.312910273.75180.2894
#Mann= 3 , 0 , 0
 9628.61   0.095       0 9628.61   0.095       010273.75   0.095       0
#XS Ineff= 2 , 0
       0                               0
Bank Sta=9628.61,10273.75
Exp/Cntr=0.3,0.1

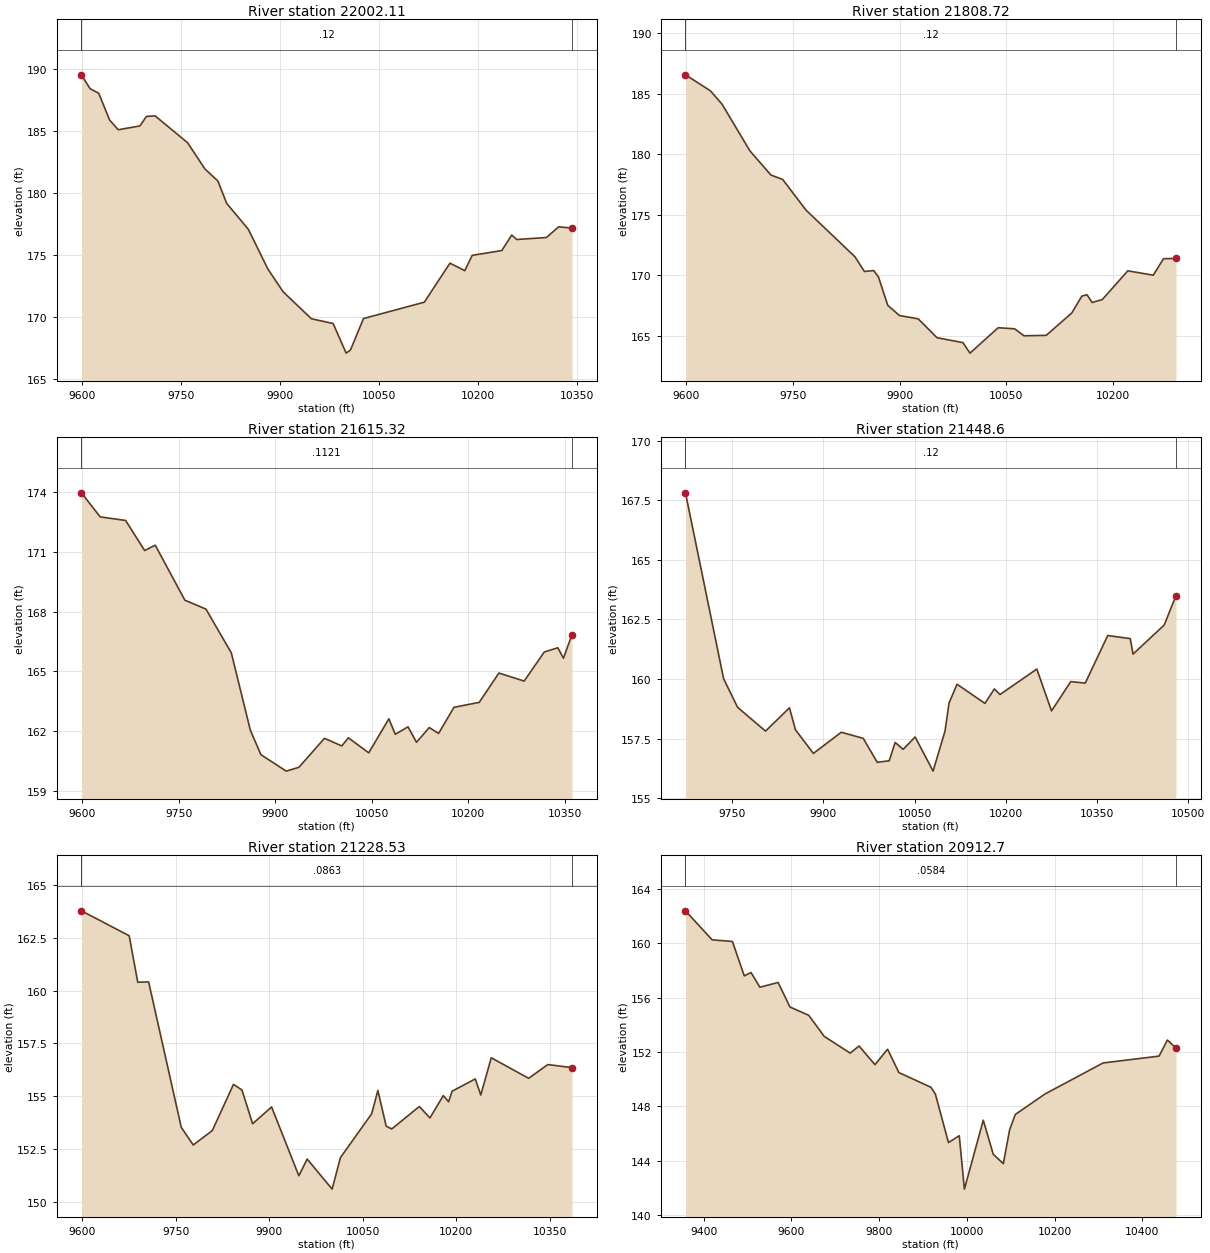
Type RM Length L Ch R = 1 ,22002.11,193.396100,193.396100,193.396100
XS GIS Cut Line= 6
1225656.34703799626875.929744808 1225652.0567392 626747.87436311
1225654.26923467626644.8550249961225667.65131502  626453.8318627
1225659.60993305626340.5181300491225560.37213868626159.555093274
#Sta/Elev= 30
9599.061189.51289612.102 188.3969625.232188.02819641.646185.87279654.777185.0845
9687.603185.39319697.451186.15949710.582186.20359759.811184.03719786.064181.9191
9805.754 180.948 9818.88179.15569851.766177.05519881.396173.84839904.442172.0187
9947.241 169.8449980.144169.46299999.836167.0739 10006.4167.329310026.11169.8623
 10118.2171.1816   10157174.326710179.45173.722910190.68174.957810235.58175.3449
10250.55176.597410258.03176.236210302.93176.393910321.64177.259710341.76177.1532
#Mann= 3 , 0 , 0
9599.061    0.12       09599.061    0.12       010341.76    0.12       0
#XS Ineff= 2 , 0
       0                               0
Bank Sta=9599.061,10341.76
Exp/Cntr=0.3,0.1

Type RM Length L Ch R = 1 ,21808.72,193.396000,193.396000,193.396000
XS GIS Cut Line= 6
1225843.96450736626884.5712361071225839.89334391626760.948525369
1225842.61386851626645.3246379321225849.38509343626555.641556501
1225868.72861213626397.2983489251225788.03531399626213.552128419
#Sta/Elev= 30
9599.052186.56249633.869185.25289650.282184.15529689.673180.27899719.217178.2877
9735.627177.93029768.444175.3942 9837.36 171.5359850.519170.32779863.679170.4027
 9870.26169.8819 9883.42167.53039899.871166.68879926.192166.41649952.646164.8568
9989.036164.4526 9998.96163.585410038.59165.682810061.72165.593210074.93165.0172
10106.08 165.05310141.92 166.89210156.25168.296510163.42168.406510170.58167.7664
10184.92168.007410220.75170.378810256.58170.021310270.91171.379910288.54171.4041
#Mann= 3 , 0 , 0
9599.052    0.12       09599.052    0.12       010288.54    0.12       0
#XS Ineff= 2 , 0
       0                               0
Bank Sta=9599.052,10288.54
Exp/Cntr=0.3,0.1

Type RM Length L Ch R = 1 ,21615.32,166.720300,166.720300,166.720300
XS GIS Cut Line= 6
1226051.90532133626895.0986795571226037.21093941626697.746281922
1226041.67020038626532.6925725941226057.76913592626451.044144884
1226046.34545514626355.1119233221225901.86690164 626190.20205918
#Sta/Elev= 30
9599.035173.98169628.119172.77119667.683172.59199697.294 171.0789713.745171.3466
9759.763168.58159792.601168.13089831.975165.92899861.504 162.0429877.913160.8098
9917.304159.97939937.039160.17249976.686161.628910003.71161.246310013.87 161.656
10045.56160.900110076.84162.611710086.75161.833410106.57162.208110119.79161.4304
10139.61162.171810154.09161.875910178.05163.190610217.31163.439310247.84164.9149
 10287.1164.509710318.38165.972910339.44166.185910348.17165.659710361.42166.8505
#Mann= 3 , 0 , 0
9599.035  0.1121       09599.035  0.1121       010361.42  0.1121       0
#XS Ineff= 2 , 0
       0                               0
Bank Sta=9599.035,10361.42
Exp/Cntr=0.3,0.1

Type RM Length L Ch R = 1 , 21448.6,220.071700,220.071700,220.071700
XS GIS Cut Line= 3
1226214.17407796626833.7883431761226214.17407796626337.599371374
1225995.26717868 626117.23309274
#Sta/Elev= 30
9673.204167.8094 9735.96160.01519758.925158.81779804.857157.82019844.227158.7966
 9854.07157.87789883.597156.88559929.529157.77329965.618157.51699988.584156.5116
10008.27156.577210018.11157.345310031.23157.056710050.92157.574810080.45 156.143
10100.13157.826810106.69158.997810119.82159.786410165.75158.982410181.25159.5884
10190.57159.354510251.08160.422310275.24158.667510306.95159.896310330.74159.8331
10367.73161.828110404.73161.697610409.36161.048910460.57 162.26710480.01163.5023
#Mann= 3 , 0 , 0
9673.204    0.12       09673.204    0.12       010480.01    0.12       0
#XS Ineff= 2 , 0
       09878.359        10139.76       0
Bank Sta=9673.204,10480.01
Exp/Cntr=0.3,0.1

Type RM Length L Ch R = 1 ,21228.53,315.828700,315.828700,315.828700
XS GIS Cut Line= 6
1226496.05115752626795.1653808481226449.91767347626641.882050453
1226416.21210555 626518.84928002 1226402.3656032626457.078020322
1226376.11444625626312.855591416 1226190.8240087626090.964264825
#Sta/Elev= 30
9599.018163.77879675.613162.59839689.318160.39639706.759160.41399759.093153.5287
9778.261152.69129808.877153.37449842.894 155.5659856.501155.29059873.509153.6959
9903.922154.49149947.631 151.2349960.989152.026110001.01150.601810014.34152.0929
10064.37154.167710074.37155.272410087.71153.583610096.56153.449210140.78154.5133
10157.88153.973110179.25155.0294 10187.8154.738610193.34155.236310230.54155.8187
 10239.4155.058410256.19156.821110316.18155.848910346.89156.499910385.64156.3544
#Mann= 3 , 0 , 0
9599.018  0.0863       09599.018  0.0863       010385.64  0.0863       0
#XS Ineff= 2 , 0
       0 9891.27        10076.01       0
Bank Sta=9599.018,10385.64
Exp/Cntr=0.3,0.1

Type RM Length L Ch R = 1 , 20912.7,264.359400,264.359400,264.359400
XS GIS Cut Line= 6
1227056.19824549 626875.177809871226869.20624529626577.525913419
 1226779.5232925 626454.893361271226709.24379364626369.140761538
1226673.78244304626314.4642538671226358.54064363626009.340400919
#Sta/Elev= 30
9358.597162.37299419.332160.24279465.626160.12079492.631157.59639508.062157.8383
9528.212156.76079569.787157.10899596.792155.30699639.612154.69639674.887153.1472
9734.205151.9162 9754.24152.44319790.569151.0674 9819.41152.20469845.099  150.49
9918.337149.40389928.438 148.8979958.131145.34289982.741145.84839994.458 141.923
10037.51146.988610060.24144.483610083.19143.794910097.68146.293310110.52147.4082
 10178.1148.912510310.55 151.19410438.27151.697610457.19152.878310476.89 152.289
#Mann= 3 , 0 , 0
9358.597  0.0584       09358.597  0.0584       010476.89  0.0584       0
#XS Ineff= 2 , 0
       0                10178.89       0
Bank Sta=9358.597,10476.89
Exp/Cntr=0.3,0.1

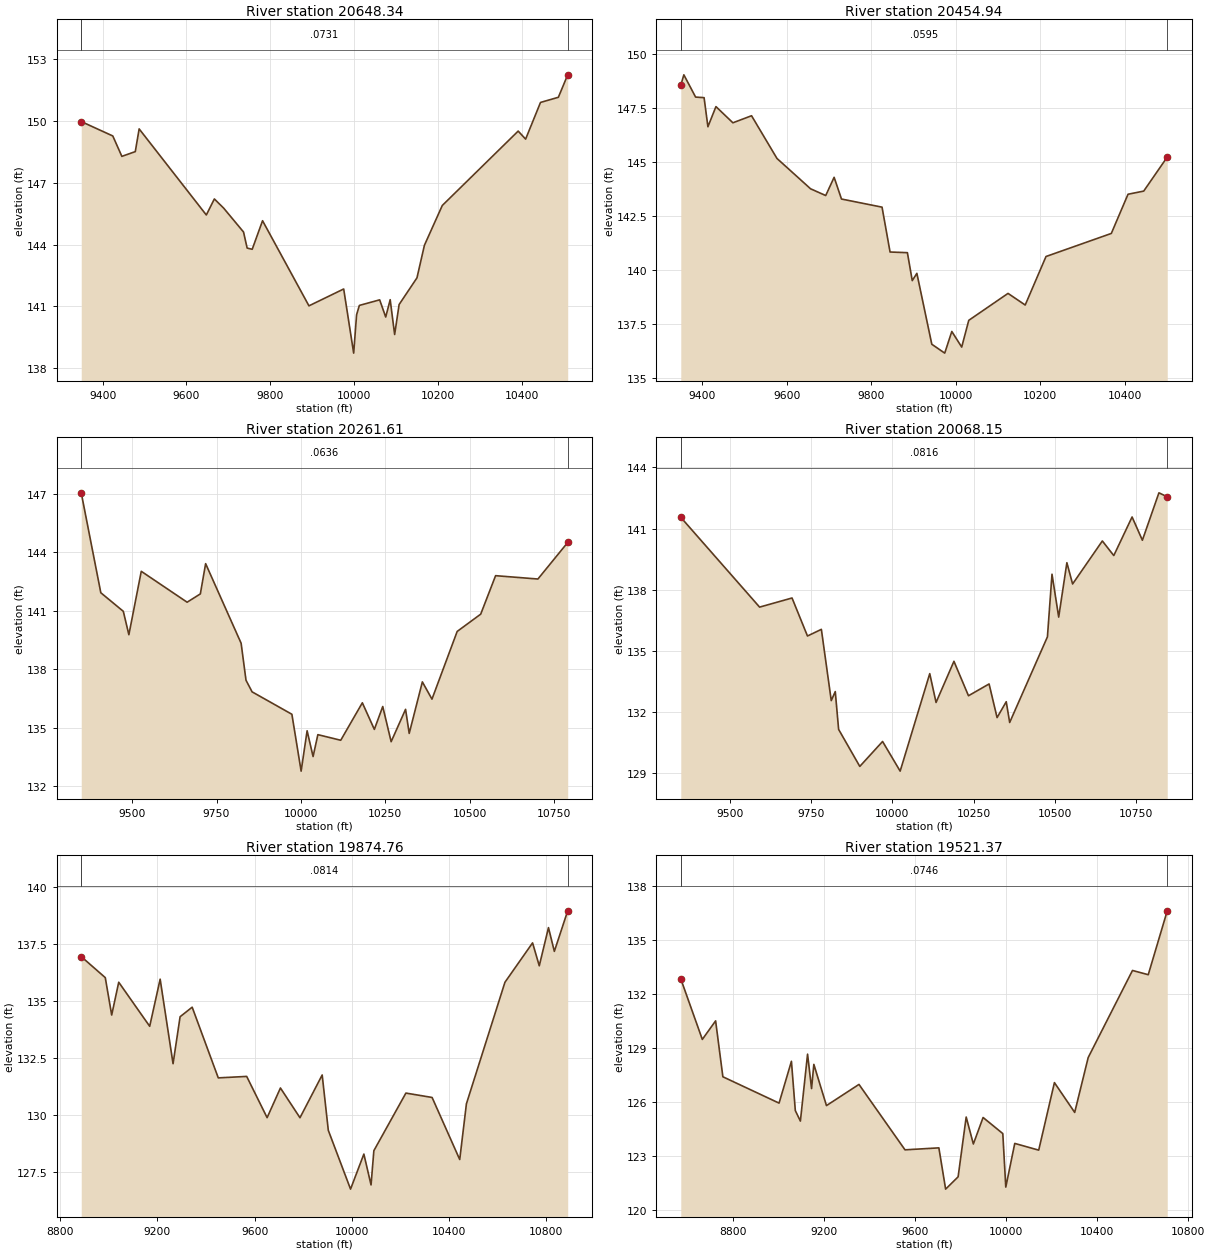
Type RM Length L Ch R = 1 ,20648.34,193.396100,193.396100,193.396100
XS GIS Cut Line= 6
1227262.81485235626620.7198660861227030.60879258  626300.2771059
1226952.96961273626215.9951574051226912.31103451626182.621841816
1226778.73875452626106.0913792221226368.96141362625936.395010903
#Sta/Elev= 30
9349.086149.9588 9424.38149.26079445.989148.27239478.043148.50249487.246149.6029
9647.527145.43149666.694146.20919688.903145.76359736.308144.60689744.888143.8289
9756.975143.76949781.678145.15399892.373141.0291 9975.25 141.8469999.079138.7382
10006.05140.599310012.66141.050110061.07141.319810075.52140.487510086.17 141.328
10096.82139.639210107.48141.092310150.09142.386210167.84143.963110210.46145.8913
10391.56 149.49710409.31149.107310444.82 150.88510487.44151.135710509.71152.2233
#Mann= 3 , 0 , 0
9349.086  0.0731       09349.086  0.0731       010509.71  0.0731       0
#XS Ineff= 2 , 0
       0                               0
Bank Sta=9349.086,10509.71
Exp/Cntr=0.3,0.1

Type RM Length L Ch R = 1 ,20454.94,193.331300,193.331300,193.331300
XS GIS Cut Line= 6
1227302.51273821626579.9010116061227037.86432984626195.279200657
1226988.11238227626103.9489517531226957.71433394625978.258885842
1226918.73868898625934.4202576731226560.70358169625773.830998808
#Sta/Elev= 30
9349.083148.53399356.342149.01749384.171147.98659404.238147.96069413.307146.6139
9432.331147.54639472.464 146.7979516.611147.12289576.749145.14719656.357143.7415
9692.181143.42929712.083144.27379729.512143.26799825.527142.89199844.503140.8154
9885.543140.78429897.051139.49019907.969139.82759943.337136.54549973.931136.1344
9990.691137.137410014.11136.414210030.82137.652410123.78138.899510164.44138.3612
10213.68140.607110368.29141.674910407.85143.489110445.03143.635410500.72145.2114
#Mann= 3 , 0 , 0
9349.083  0.0595       09349.083  0.0595       010500.72  0.0595       0
#XS Ineff= 2 , 0
       0                10115.78       0
Bank Sta=9349.083,10500.72
Exp/Cntr=0.3,0.1

Type RM Length L Ch R = 1 ,20261.61,193.460700,193.460700,193.460700
XS GIS Cut Line= 6
1227477.68965364626555.555773592 1227316.5664349626337.816500859
1227217.66346826626176.4418321681227193.58102967626124.172940997
1227108.49231559625888.4885910151226487.75819167625627.940218747
#Sta/Elev= 30
9349.081147.04529407.103141.91839473.814140.96439490.268139.76369527.021143.0181
9662.904141.43269702.089141.85839717.763143.41079822.965139.32669837.414137.4281
9855.476136.83289973.424 135.68310000.83132.765110018.54134.835610036.25133.5131
10050.42134.6368 10118.2134.348810182.25136.271610217.83134.907110242.74136.0803
10267.64134.274610310.34135.935610321.16134.700310360.16137.343910388.62136.4583
10463.34139.932710533.09140.8201 10577.2142.794210702.63142.622410790.92144.4975
#Mann= 3 , 0 , 0
9349.081  0.0636       09349.081  0.0636       010790.92  0.0636       0
#XS Ineff= 2 , 0
       0                10201.46       0
Bank Sta=9349.081,10790.92
Exp/Cntr=0.3,0.1

Type RM Length L Ch R = 1 ,20068.15,193.396000,193.396000,193.396000
XS GIS Cut Line= 6
1227772.62989731626362.5951226431227613.24652503626199.201587286
1227396.27023389625972.030875964 1227352.5083875625931.789056837
1227150.51916397625775.9151528031226554.45111969625544.574058697
#Sta/Elev= 30
9349.033141.55049591.473137.13869691.224137.58679738.725135.71919781.475136.0461
9811.871132.54479824.226132.98879834.555131.13039899.684129.31259969.749130.5377
10023.83 129.08110114.85133.869910134.25 132.45410189.27134.475910233.99132.7836
10297.34133.363510321.97131.710210350.13132.490910360.69131.470510476.82135.6774
 10490.9138.756510511.49136.647710536.65139.320410554.25 138.27510645.75140.3885
10680.94139.670710737.25141.567910768.92140.424210819.79142.753510845.41142.5584
#Mann= 3 , 0 , 0
9349.033  0.0816       09349.033  0.0816       010845.41  0.0816       0
#XS Ineff= 2 , 0
       0                10203.91       0
Bank Sta=9349.033,10845.41
Exp/Cntr=0.3,0.1

Type RM Length L Ch R = 1 ,19874.76,353.390800,353.390800,353.390800
XS GIS Cut Line= 6
1228372.04292139626372.101732463 1227976.1082651 626067.18653737
1227528.56476828 625847.18842575 1227415.5667491625733.315326303
1227231.80117005625617.5194487271226635.73312572625425.777280658
#Sta/Elev= 30
8886.567136.93898985.535136.01779011.905134.37739040.892135.81589168.356133.8821
9211.373135.94989264.504132.24069293.491 134.3029343.183134.72079450.598131.6195
9567.583131.68359651.666129.87429706.503131.17549786.931129.87029878.326131.7468
9903.521129.31859995.091126.7388 10049.9128.276510079.43 126.92310091.07128.4258
10222.92130.952610330.74130.760410444.47128.036610472.04130.483510630.58135.8142
10744.31137.542310771.88136.536510809.79138.210610833.92  137.1710888.92138.9483
#Mann= 3 , 0 , 0
8886.567  0.0814       08886.567  0.0814       010888.92  0.0814       0
#XS Ineff= 2 , 0
       09855.691        10229.65       0
Bank Sta=8886.567,10888.92
Exp/Cntr=0.3,0.1

Type RM Length L Ch R = 1 ,19521.37,169.139800,169.139800,169.139800
XS GIS Cut Line= 6
1228642.82581854626267.429352045 1228392.4600375625948.955324739
1227644.09570587625453.7201327531227543.29544479625435.809511289
1227313.08317605625425.7772806581226814.97036982625379.925892621
#Sta/Elev= 30
8572.399132.86148666.904129.49538725.298130.52688757.149127.4179 9003.84125.9541
9058.117 128.2799075.181125.53769097.458124.95569128.931128.67569146.521126.7622
9156.471128.10739211.916 125.8169354.597126.99329556.727123.35629705.353123.4661
9735.078121.1719 9789.87121.85629825.277125.18029856.751123.68029899.513125.1543
9986.016124.26049999.142 121.28410038.52123.712610143.64 123.33910212.66127.0933
10301.62125.436710360.92128.488510555.31133.3292 10624.5133.092510707.95136.6446
#Mann= 3 , 0 , 0
8572.399  0.0746       08572.399  0.0746       010707.95  0.0746       0
#XS Ineff= 2 , 0
       09786.203        10148.14       0
Bank Sta=8572.399,10707.95
Exp/Cntr=0.3,0.1