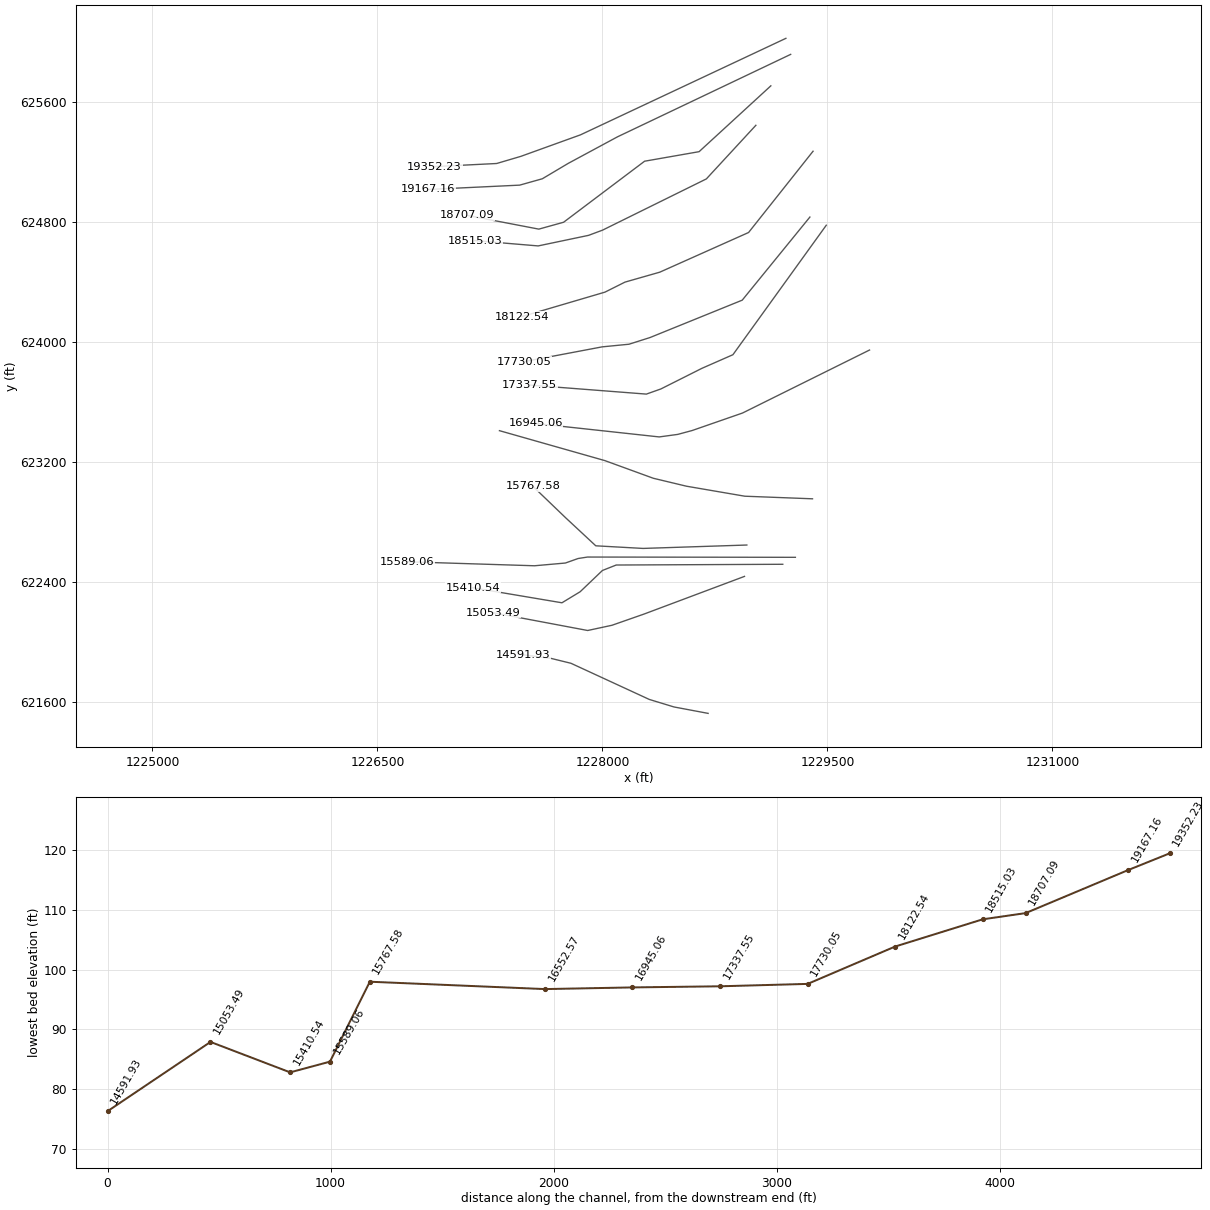
HEC-RAS study 264_ras.prj: 264

--- 264_ras.g01 (geometry) --- (continued)

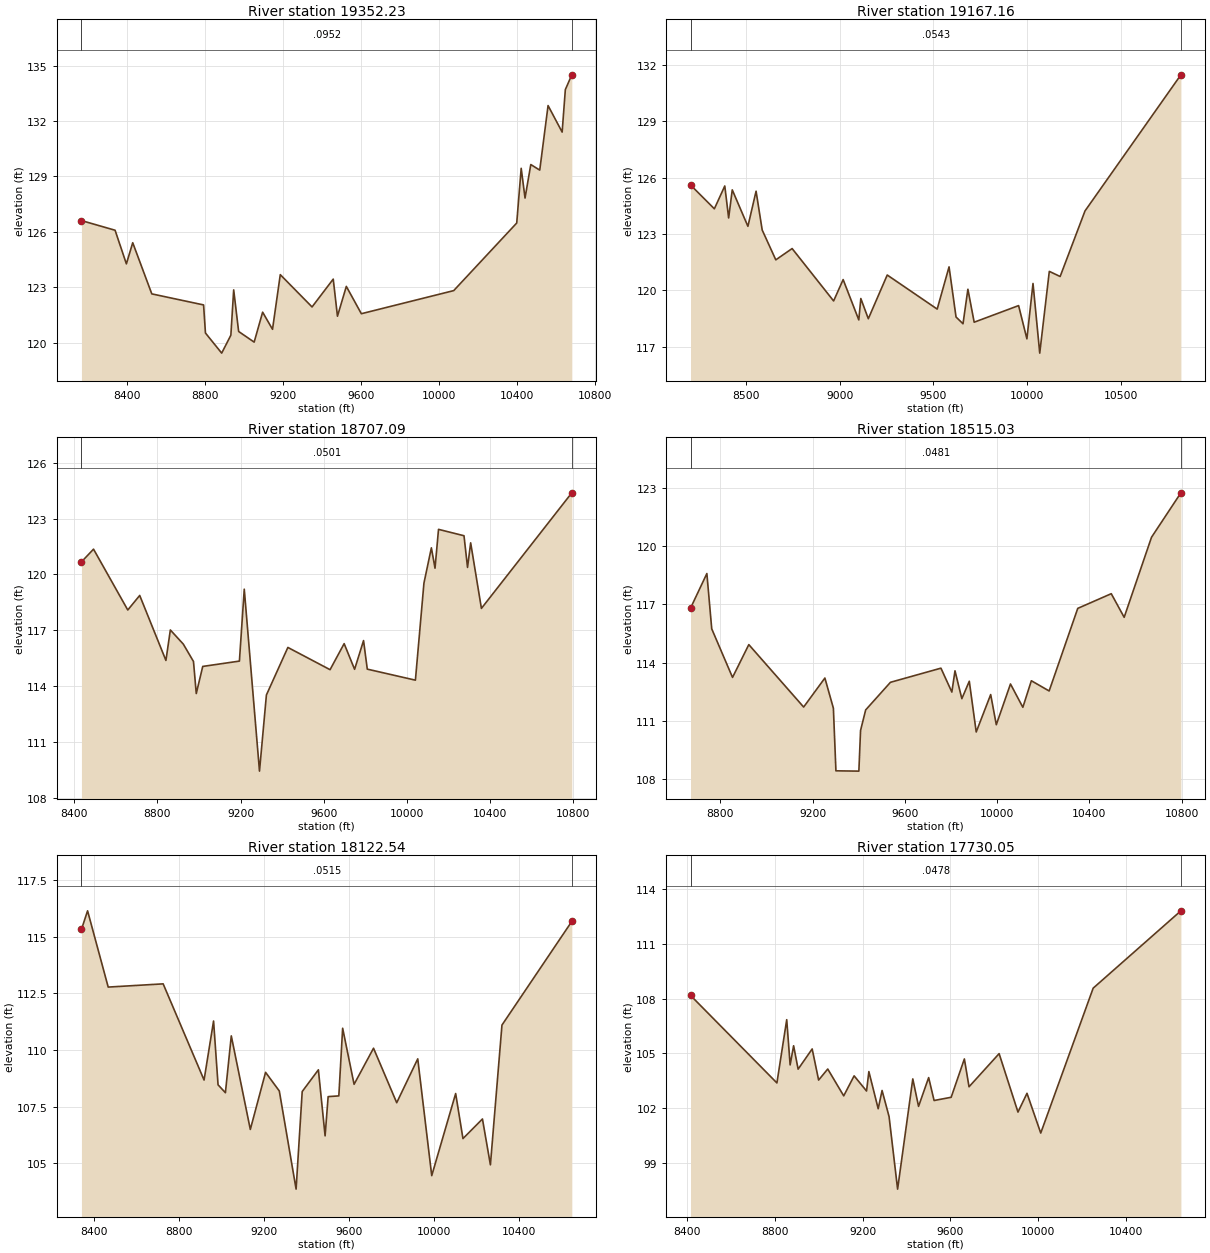
Type RM Length L Ch R = 1 ,19352.23,185.069800,185.069800,185.069800
XS GIS Cut Line= 5
1229223.07488385626023.9522932771227853.50852522625380.482224852
1227456.37310854625237.253058195 1227294.6977613625189.510002643
1226881.28630301625168.893683195
#Sta/Elev= 30
8164.997126.61188337.771126.08818395.769124.26748428.393125.41218526.266122.6418
8792.168122.04368801.758120.52338885.131119.43348932.255120.40438946.755122.8575
8972.129120.60599051.877120.02989095.376121.65079146.124 120.7239185.998123.6828
9349.119121.93419457.866123.44179479.616 121.4329525.119123.04729602.271121.5675
10076.55122.818910399.99126.478210422.98129.441710442.69127.830810472.26129.6454
10518.25129.343610560.95132.839610633.22131.403610649.64133.703110682.87134.5041
#Mann= 3 , 0 , 0
8164.997  0.0952       08164.997  0.0952       010682.87  0.0952       0
#XS Ineff= 2 , 0
       09700.049        10118.93       0
Bank Sta=8164.997,10682.87
Exp/Cntr=0.3,0.1

Type RM Length L Ch R = 1 ,19167.16,460.066000,460.066000,460.066000
XS GIS Cut Line= 6
1229254.93169528625917.004426345  1228099.810186625367.041199476
 1227771.1350503625189.8723218741227599.37360919625087.764323443
 1227448.3710278625045.3321989921226839.07599041625016.318149567
#Sta/Elev= 30
 8203.06125.60458330.452124.33478386.099125.55178406.773 123.848 8426.07125.3432
8509.645123.4031 8553.25 125.2738585.953123.20678658.627121.61788745.836122.2193
8967.492119.42899018.364120.56729101.939118.42119112.841119.55889152.811118.4827
9253.935120.80989520.777118.99569584.138121.24469621.409118.5751 9658.68118.2144
 9684.77120.05299718.314118.29749955.602 119.1829999.921117.4121 10032.6120.3596
10068.54116.651510119.66121.004310177.59120.731610310.24124.220510822.57 131.469
#Mann= 3 , 0 , 0
 8203.06  0.0543       0 8203.06  0.0543       010822.57  0.0543       0
#XS Ineff= 2 , 0
       0 9712.38                       0
Bank Sta=8203.06,10822.57
Exp/Cntr=0.3,0.1

Type RM Length L Ch R = 1 ,18707.09,192.056200,192.056200,192.056200
XS GIS Cut Line= 6
1229122.70575202625707.3191404941228644.40538234625268.372598648
1228281.13927874625204.8010305321227741.04944068624797.839479387
1227575.81160605624752.0309707821227098.09430215624843.647987992
#Sta/Elev= 30
8434.058 120.673 8492.26121.35728657.022118.09148714.419118.87178840.577115.3835
 8861.86117.01928924.203116.25998973.186115.32638986.545113.60569017.716115.0619
9194.105115.3482 9217.42119.20839290.695109.44219324.002113.52949427.254116.0813
9630.249114.88759698.008116.28539748.272114.90739791.355116.44949809.306 114.917
10040.84114.3246 10081.9119.533310117.68121.428610135.21120.335110152.03122.4199
 10274.6122.077210291.62120.376610306.68121.696210358.41118.176810793.33124.3808
#Mann= 3 , 0 , 0
8434.058  0.0501       08434.058  0.0501       010793.33  0.0501       0
#XS Ineff= 2 , 0
       09719.191        10116.76       0
Bank Sta=8434.058,10793.33
Exp/Cntr=0.3,0.1

Type RM Length L Ch R = 1 ,18515.03,392.492900,392.492900,392.492900
XS GIS Cut Line= 6
1229022.94462824625444.2517206221228692.84086278 625086.73954685
1228000.62867662624745.1562640821227907.70477131624710.537656292
1227571.51827222624640.0512222651227148.43500999624675.481840268
#Sta/Elev= 30
 8670.83 116.8078741.744118.59518762.803115.74298852.978 113.238 8923.56114.9293
 9161.29111.71019253.354 113.2069290.179111.65179301.227108.42099400.656108.4055
9408.021110.50219430.116111.56069537.595112.98569756.493113.71499803.792112.4825
9817.394113.57869847.072 112.1419879.402113.0401 9909.43110.42299972.124112.3543
9996.457110.798410057.96112.899210111.59111.696810148.47113.065510225.57112.5394
 10349.6116.797710494.86117.554710550.83116.337810669.36120.464910796.73122.7564
#Mann= 3 , 0 , 0
 8670.83  0.0481       0 8670.83  0.0481       010796.73  0.0481       0
#XS Ineff= 2 , 0
       09747.333        10096.27       0
Bank Sta=8670.83,10796.73
Exp/Cntr=0.3,0.1

Type RM Length L Ch R = 1 ,18122.54,392.492900,392.492900,392.492900
XS GIS Cut Line= 6
1229404.23698229625271.3998161851228974.37209305624729.527878329
1228382.25417858624464.9822861851228150.38502163 624398.77694577
  1228017.071623624332.0349812661227462.50156757624168.813442796
#Sta/Elev= 30
8341.498115.3246 8370.44 116.1498467.567112.77938726.404112.92178919.043108.6716
8963.793111.28038984.909108.46069019.551108.11179047.229110.62299136.868106.4887
9208.735 109.0129273.416108.18739352.471103.85139381.218108.16319457.416109.1239
 9489.02106.20519503.393107.93839553.701107.97159571.668110.96059625.569108.4834
9717.114110.07819826.296107.66939925.374109.60839991.224104.446710103.91108.0749
10138.26106.084710230.12106.950710267.53104.925310321.95111.100510650.93115.6814
#Mann= 3 , 0 , 0
8341.498  0.0515       08341.498  0.0515       010650.93  0.0515       0
#XS Ineff= 2 , 0
       09865.172                       0
Bank Sta=8341.498,10650.93
Exp/Cntr=0.3,0.1

Type RM Length L Ch R = 1 ,17730.05,392.492900,392.492900,392.492900
XS GIS Cut Line= 6
1229383.04645962624832.4532743391228931.99104768624278.472466394
1228317.64540458624029.3940999511228177.07139781623984.665836856
1227998.48372352623967.1341807251227476.35598591623868.336020172
#Sta/Elev= 30
8414.901108.17088808.871 103.3918853.577106.84438869.165104.37488885.026105.4209
8905.539104.14448969.642105.2473 8999.07103.5492 9040.64104.15169113.488102.6867
9160.936103.7789 9217.58102.95159228.201 104.0129270.684101.98389288.385102.9802
9320.247101.55749359.18997.596129428.494103.61279454.689102.11259500.798 103.683
 9525.58102.43339603.465102.60949663.649104.7017 9684.89103.18159822.068104.9914
 9908.08101.80049949.189102.8255 10011.9100.656810250.98 108.56510650.97112.7861
#Mann= 3 , 0 , 0
8414.901  0.0478       08414.901  0.0478       010650.97  0.0478       0
#XS Ineff= 2 , 0
       09786.566                       0
Bank Sta=8414.901,10650.97
Exp/Cntr=0.3,0.1

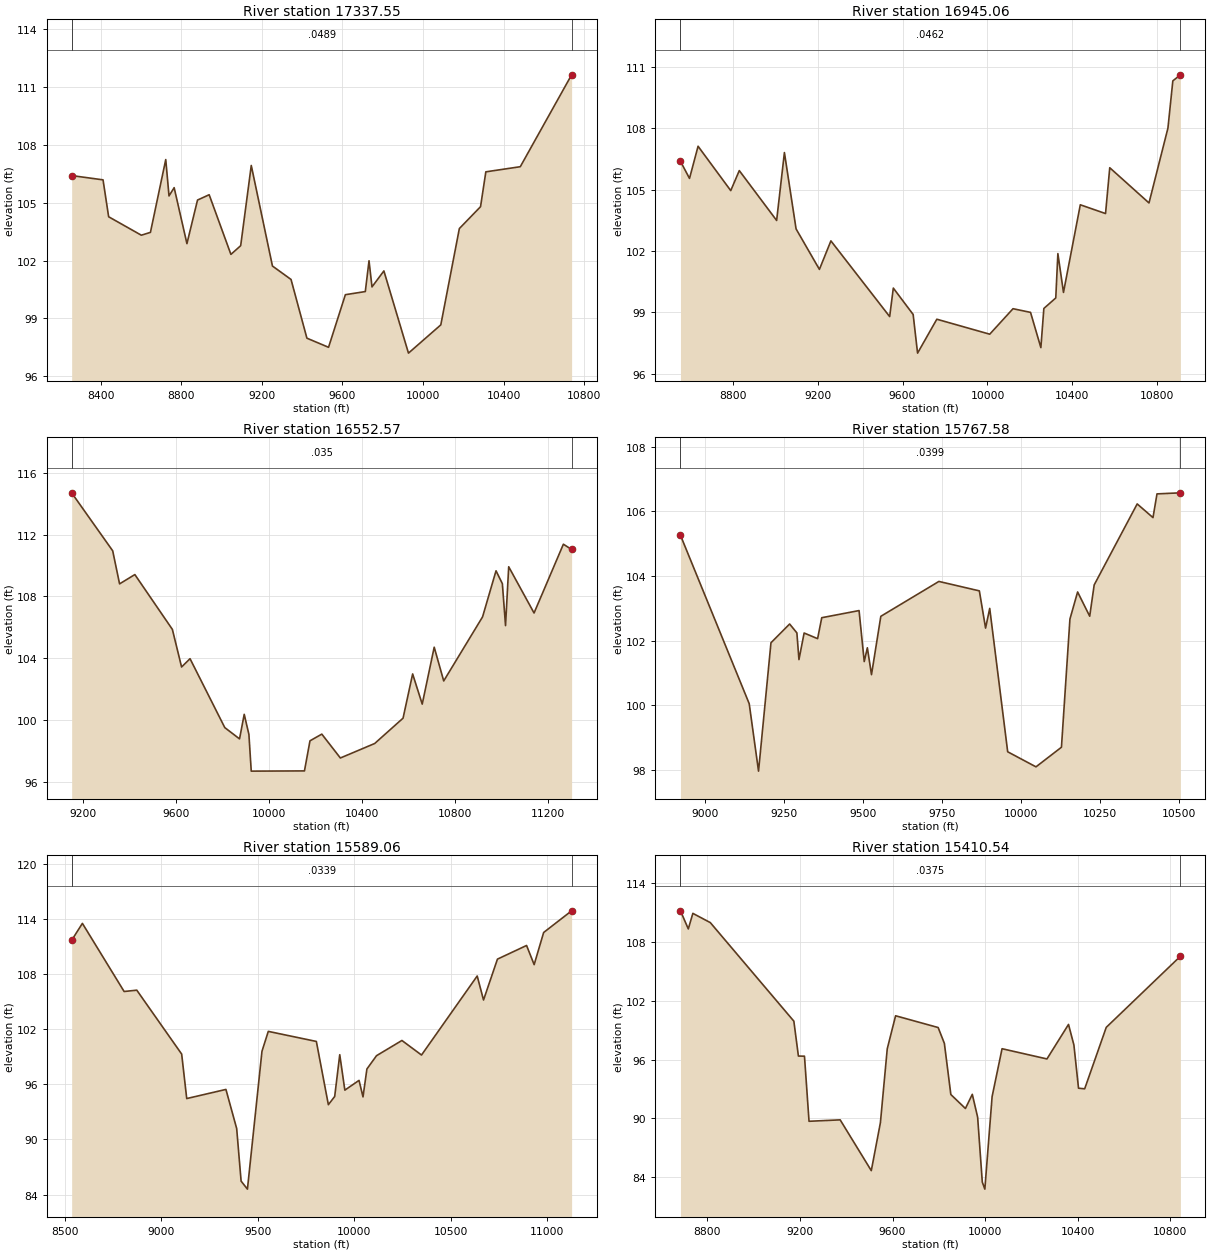
Type RM Length L Ch R = 1 ,17337.55,392.492900,392.492900,392.492900
XS GIS Cut Line= 6
1229492.33703387624778.0173384551228869.94621485623914.765629902
1228662.66897231 623823.744322331228389.44275257623686.406137735
1228292.80280635623652.1878342481227513.16196018623712.602691799
#Sta/Elev= 30
8255.374106.41428411.205106.19228439.009104.27618601.303103.31858646.574103.4647
8722.642 107.2468738.821105.35698764.382105.78738827.803102.88038880.383 105.143
8938.289105.41939046.213102.32199094.749 102.7749147.329106.9392 9252.49101.7181
9344.785101.02019423.61697.972289531.11397.497929614.584100.22899713.625100.3924
9732.085101.99119746.853100.63399805.924 101.4649928.00797.1958710088.5898.66267
10180.67103.663110285.91104.798810312.22106.608410483.24106.874310738.18111.6451
#Mann= 3 , 0 , 0
8255.374  0.0489       08255.374  0.0489       010738.18  0.0489       0
#XS Ineff= 2 , 0
       09779.166                       0
Bank Sta=8255.374,10738.18
Exp/Cntr=0.3,0.1

Type RM Length L Ch R = 1 ,16945.06,392.492900,392.492900,392.492900
XS GIS Cut Line= 6
1229780.72151327623946.0279399161228934.01115507623526.030813202
1228597.96874854 623409.326038391228501.69534427623383.465569094
1228378.49272311623366.6715343891227554.84504017623456.251749694
#Sta/Elev= 30
8554.584106.3813 8597.19105.54448637.476107.11658791.291104.94928831.577105.9262
9007.366103.49059043.989 106.8089098.923103.07759208.792   101.19262.898102.4932
9539.51398.794169556.723100.18719650.07898.897619670.916 97.00889761.57698.66562
10010.6597.9337410120.2899.1790510202.7998.9994110251.3997.2775210265.4999.19117
10321.5999.7045410331.49101.871510357.8999.97597 10437.1104.2566 10555.9103.8277
10575.71106.066910760.52 104.34610849.62108.001210872.72110.311110908.41110.6063
#Mann= 3 , 0 , 0
8554.584  0.0462       08554.584  0.0462       010908.41  0.0462       0
#XS Ineff= 2 , 0
       09882.341                       0
Bank Sta=8554.584,10908.41
Exp/Cntr=0.3,0.1

Type RM Length L Ch R = 1 ,16552.57,784.985800,784.985800,784.985800
XS GIS Cut Line= 6
1229400.54871896622954.156069085 1228949.4254407622971.421850204
1228560.41422209623038.1232824921228339.37243807623091.024059534
1228016.26086298623208.7721321731227313.47539088623408.368721783
#Sta/Elev= 30
9152.364114.69059328.732110.94679358.275108.81329423.942 109.414 9585.14105.8765
9624.736  103.459661.083103.98479810.42899.537489873.81298.809389893.931100.3957
9914.06199.097929924.12696.72848 10152.896.7425310176.5298.6841910227.3899.11715
 10307.197.5760410454.65 98.511610576.52100.145710617.71103.000710658.89 101.053
10710.37104.727410751.26102.549610918.14106.682510976.03109.657511003.28108.8262
 11016.9106.121311030.52109.9188 11139.5106.934211265.51 111.37411300.88 111.034
#Mann= 3 , 0 , 0
9152.364   0.035       09152.364   0.035       011300.88   0.035       0
#XS Ineff= 2 , 0
       09897.401        10502.61       0
Bank Sta=9152.364,11300.88
Exp/Cntr=0.3,0.1

Type RM Length L Ch R = 1 ,15767.58,178.523700,178.523700,178.523700
XS GIS Cut Line= 5
1228962.82090682622646.0025279521228271.06512046622623.350575224
1227955.68024048622640.7751542481227755.29758197622827.218149573
1227537.49034443623036.313097611
#Sta/Elev= 30
 8921.47105.26029139.228100.04829168.772 97.96129208.163101.93379267.249102.5141
9290.228102.23939296.793101.41329313.206102.23539355.879102.0609 9369.01 102.709
9487.183102.92989503.596101.35149513.444 101.7799526.574100.94659556.118102.7521
9740.068103.83159868.215103.5396 9887.93102.38799901.074102.99689957.96598.55986
10047.5998.0935310128.2598.7003510155.14102.666710179.46103.505610217.74102.7553
10231.96103.723510368.18106.230510418.21105.807510430.93106.5408 10505.1106.5739
#Mann= 3 , 0 , 0
 8921.47  0.0399       0 8921.47  0.0399       0 10505.1  0.0399       0
#XS Ineff= 2 , 0
       09894.914        10204.91       0
Bank Sta=8921.47,10505.1
Exp/Cntr=0.3,0.1

Type RM Length L Ch R = 1 ,15589.06,178.523700,178.523700,178.523700
XS GIS Cut Line= 6
 1229286.4307501 622564.059884221227900.39221783 622565.85506492
1227838.03071817622556.1466159151227752.94688609622525.970701703
1227547.15780734622507.7414170971226700.50732377622534.277708151
#Sta/Elev= 30
8534.042111.6615 8589.73113.50368806.265106.09038871.881106.23559104.82199.28289
9131.06794.442259334.47995.434539390.25391.179689413.21985.459339446.02784.58689
9521.48699.586339554.295101.75139803.638100.65659865.97493.774899898.79794.66722
9925.082  99.2139951.46695.3566210025.0796.4198810045.7194.6254910065.9397.65635
10115.88 99.106310247.56100.7615 10349.399.1778510638.21107.777510671.05105.1666
 10743.3109.612610894.35111.098410933.74 109.01610982.97112.510211128.09114.8691
#Mann= 3 , 0 , 0
8534.042  0.0339       08534.042  0.0339       011128.09  0.0339       0
#XS Ineff= 2 , 0
       09698.713        10215.32       0
Bank Sta=8534.042,11128.09
Exp/Cntr=0.3,0.1

Type RM Length L Ch R = 1 ,15410.54,357.047400,357.047400,357.047400
XS GIS Cut Line= 6
1229202.29000685622517.6374052021228091.89577913622512.695467362
1228000.08070913622476.4273801051227851.55837189622334.595755432
1227730.10330188622260.9381637261227136.48968953622360.961538434
#Sta/Elev= 30
8683.741111.16538717.624109.31788737.309110.90698812.769109.96249173.66599.91687
 9193.3596.360259219.59796.345799239.28289.709489373.79789.854799508.31384.67654
9547.68389.563399577.21197.09518  9613.3100.46599797.19299.267419824.05397.65168
9852.02692.437779915.00891.012489944.68592.456269967.785 90.13019987.93883.50822
9998.94282.7924610030.3492.2288910073.3297.1067510267.2996.0645710360.4599.58223
10383.7497.49016 10403.793.0836510430.3293.0190510523.4899.2832310843.98106.5364
#Mann= 3 , 0 , 0
8683.741  0.0375       08683.741  0.0375       010843.98  0.0375       0
#XS Ineff= 2 , 0
       09718.538        10225.48       0
Bank Sta=8683.741,10843.98
Exp/Cntr=0.3,0.1

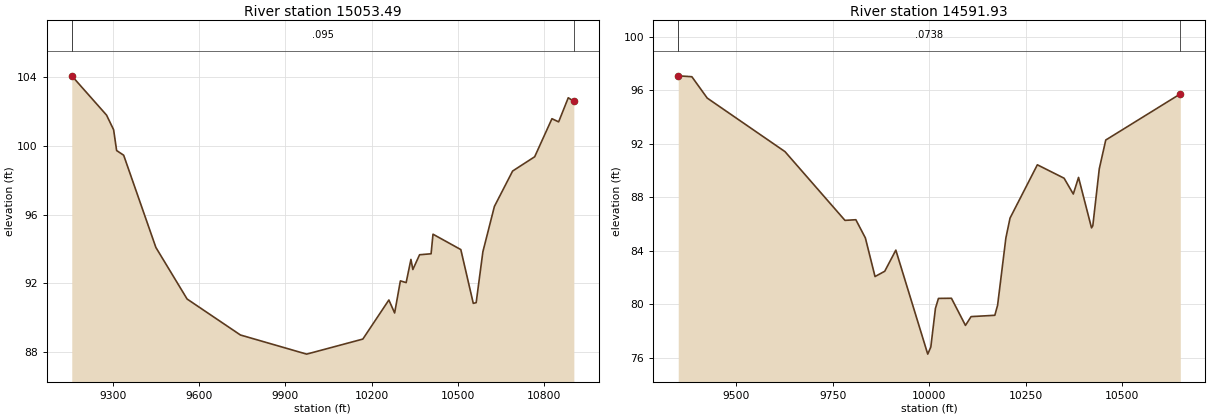
Type RM Length L Ch R = 1 ,15053.49,461.563000,461.563000,461.563000
XS GIS Cut Line= 5
1228947.13878569622436.9075799291228278.03495201  622185.9936423
1228063.71263033622111.0679526031227901.66404557622076.218794584
1227272.63674361622194.705931798
#Sta/Elev= 30
 9156.63104.06779277.716101.78249302.244100.93589312.75699.722559337.28399.45056
9449.40994.087169558.03191.089559743.73988.996699974.15887.8847210169.7288.75973
10260.3291.0323810280.3790.27738 10300.492.1446810320.4492.0428610337.1393.39138
10343.81 92.804610367.1893.6635810407.2493.7189910413.9194.8584210510.7393.96384
10554.1390.8367710564.1590.8770510587.5293.8368210627.5896.4715210691.0198.53083
 10767.899.3616910827.89101.574310851.26 101.39110884.65102.791610904.12 102.587
#Mann= 3 , 0 , 0
 9156.63   0.095       0 9156.63   0.095       010904.12   0.095       0
#XS Ineff= 2 , 0
       09761.249        10382.93       0
Bank Sta=9156.63,10904.12
Exp/Cntr=0.3,0.1

Type RM Length L Ch R = 1 ,14591.93,549.786500,549.786500,549.786500
XS GIS Cut Line= 6
1228704.61589857621523.6642855561228476.95926492621566.458429745
1228312.47555714621616.5713201021227789.86795884621857.745604581
1227658.11606909621890.056218814 1227474.2267594621913.882575781
#Sta/Elev= 30
9349.08697.087649384.42297.020659424.28895.423459625.92591.421949781.42486.28395
9809.63786.332759834.32384.971959859.36482.085899884.538 82.48169913.30884.05968
9996.047 76.288110004.03   76.8210016.0179.71008 10023.880.4523710057.4880.46322
10093.8478.4352310108.3979.0914710169.9879.1900210177.1579.9405210198.6784.97593
10209.4286.4550710280.25 90.438510349.5589.4363610373.4188.2538810387.04 89.4935
10420.6985.7246610424.0585.8814610440.8290.13816 10457.692.2884110650.9295.73601
#Mann= 3 , 0 , 0
9349.086  0.0738       09349.086  0.0738       010650.92  0.0738       0
#XS Ineff= 2 , 0
       0                10303.56       0
Bank Sta=9349.086,10650.92
Exp/Cntr=0.3,0.1