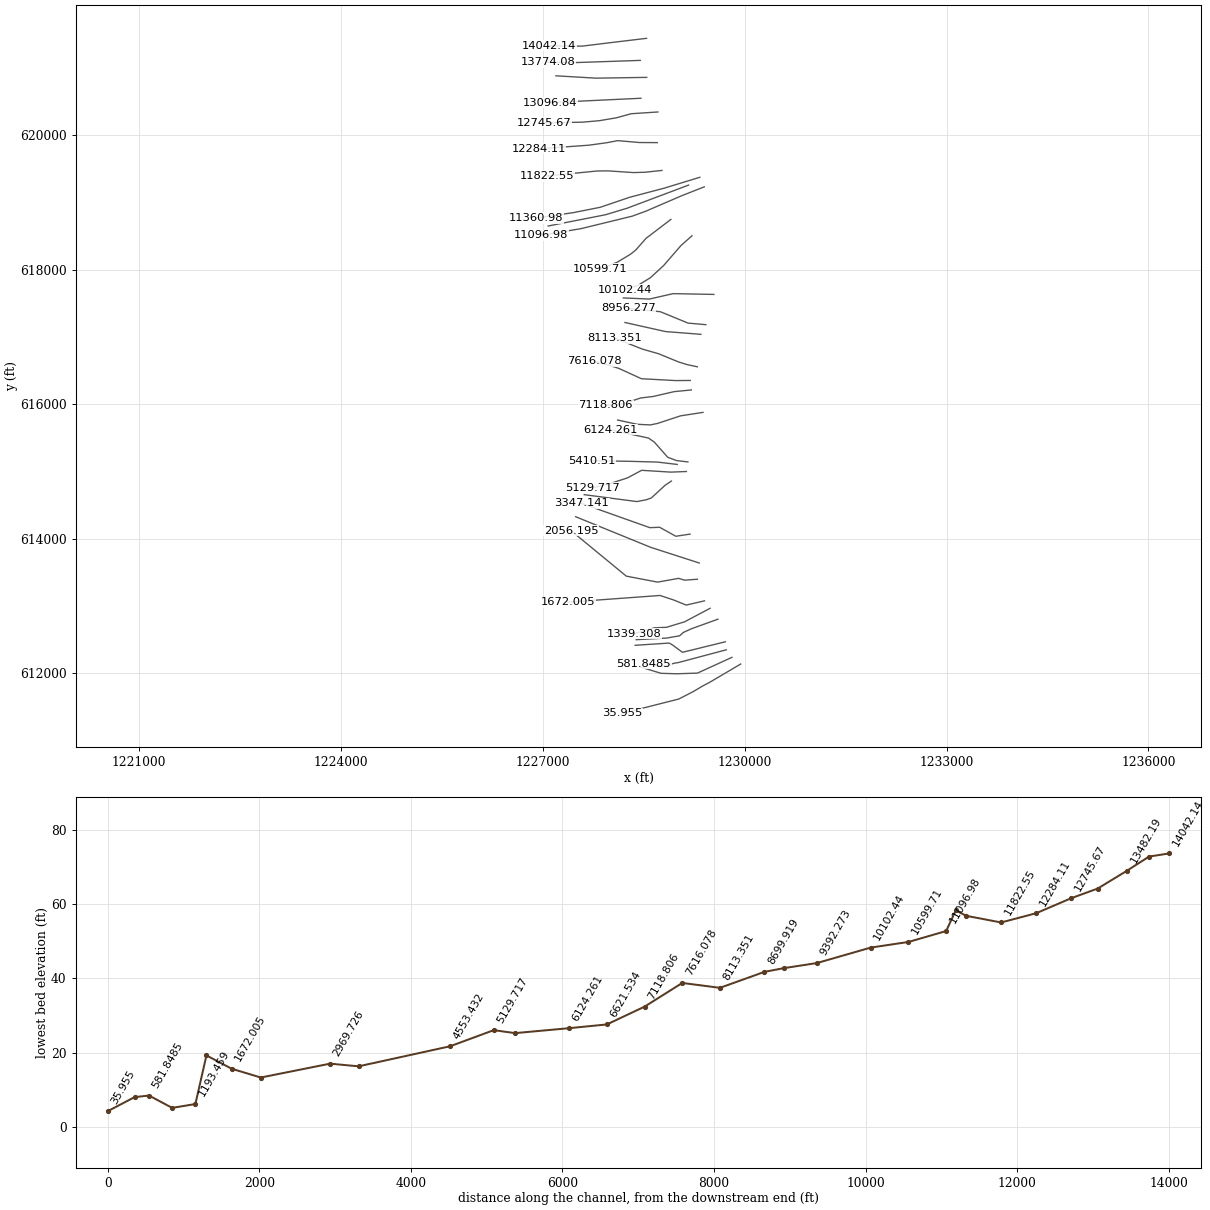
HEC-RAS study 264_ras.prj: 264

--- 264_ras.g01 (geometry) --- (continued)

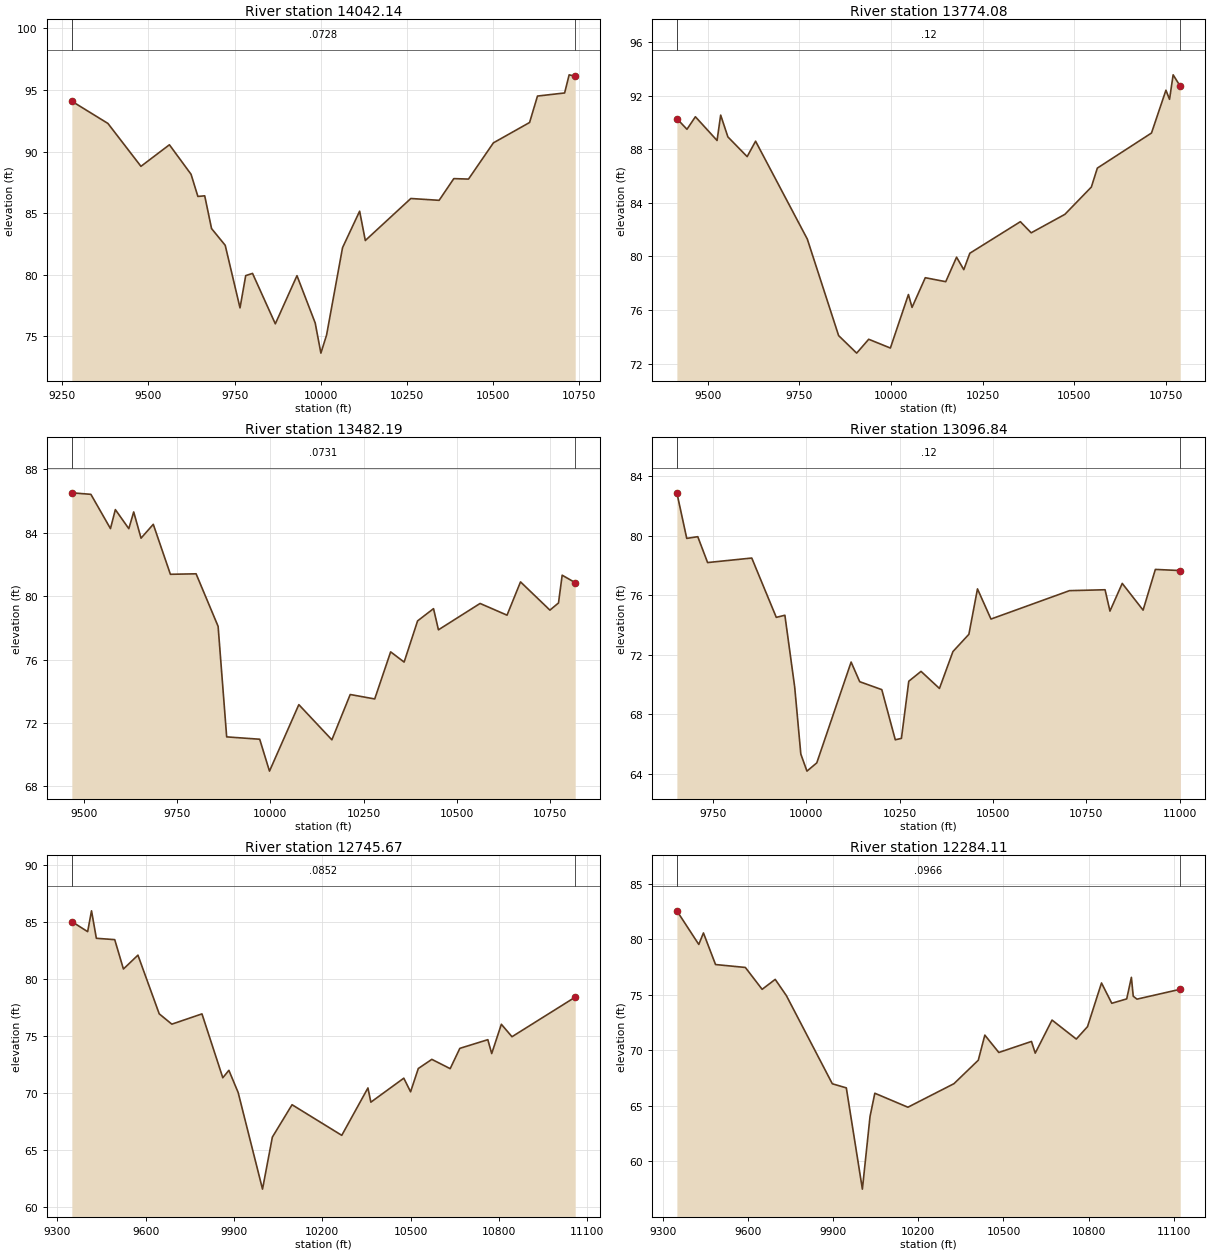
Type RM Length L Ch R = 1 ,14042.14,268.059000,268.059000,268.059000
XS GIS Cut Line= 4
 1228540.7696805 621438.314767511228006.91117153621374.483858824
 1227583.3060503621322.2585699111227087.16580558 621328.06137979
#Sta/Elev= 30
9277.67994.084679382.40892.28111 9478.23 88.79699560.835 90.54799623.61588.15296
 9643.4486.351819663.26586.40224 9683.0983.743659722.74182.383569765.69577.30132
9782.21679.922239802.04180.100189868.14976.005849930.95779.917279983.84876.07663
10000.3873.62595 10016.975.0990910063.18 82.189210112.7785.15406 10129.382.77292
10261.3886.1855510343.4186.0358910386.0687.8000110428.71 87.7616 10500.990.70322
10605.8992.3558310628.8694.50517 10707.694.7561710720.7396.2293110738.3396.11137
#Mann= 3 , 0 , 0
9277.679  0.0728       09277.679  0.0728       010738.33  0.0728       0
#XS Ineff= 2 , 0
       0                               0
Bank Sta=9277.679,10738.33
Exp/Cntr=0.3,0.1

Type RM Length L Ch R = 1 ,13774.08,291.890400,291.890400,291.890400
XS GIS Cut Line= 3
1228447.92472246621110.4560092841227504.96811694621078.540554941
1227075.56018582 621084.34336482
#Sta/Elev= 30
9416.06690.295459443.62989.499419466.608 90.43619525.69788.661989535.54590.55857
9555.24288.930349607.76587.457329630.74488.610049771.90181.293159857.25174.08584
9906.49272.775879939.31973.811849998.40873.1564110047.6577.15457 10057.576.19233
10093.6178.4097110149.4178.1134410178.9679.9432610198.6579.0120510215.07 80.2369
10352.9482.5952310382.47 81.763310474.3583.1442910546.5385.1821910562.9486.60067
10710.5989.2202210749.9692.41982 10759.8 91.739210769.65 93.568110789.01 92.7171
#Mann= 3 , 0 , 0
9416.066    0.12       09416.066    0.12       010789.01    0.12       0
#XS Ineff= 2 , 0
       0                               0
Bank Sta=9416.066,10789.01
Exp/Cntr=0.3,0.1

Type RM Length L Ch R = 1 ,13482.19,385.352200,385.352200,385.352200
XS GIS Cut Line= 3
1228543.67108542620858.0337795171227789.30580106620846.428159758
1227194.51778835620881.245019034
#Sta/Elev= 30
9467.28386.524519518.40586.429569570.90484.267359584.029 85.46619620.12384.26173
9633.247 85.31879652.93583.662379685.74784.537049731.68481.38267 9800.5981.41335
9859.652 78.0979 9882.6271.121169971.21370.972819997.46368.9599410076.2173.15562
10164.81 70.936210214.0273.7949710279.7473.5156810322.4676.4868910358.6275.84219
10394.7778.4422310437.4979.2157610450.6477.8779710562.3879.5423310634.68 78.8031
10670.8380.90375 10749.779.1215810772.7179.5733710782.5781.3259110817.5480.85559
#Mann= 3 , 0 , 0
9467.283  0.0731       09467.283  0.0731       010817.54  0.0731       0
#XS Ineff= 2 , 0
       0                               0
Bank Sta=9467.283,10817.54
Exp/Cntr=0.3,0.1

Type RM Length L Ch R = 1 ,13096.84,351.164000,351.164000,351.164000
XS GIS Cut Line= 2
1228456.62893724620547.5834509131227110.37704509620483.752542257
#Sta/Elev= 30
9653.72982.874969680.16879.812679709.72979.926259736.005  78.1889854.24778.49178
9919.93874.504389942.92974.646369969.20669.821099985.62865.3135910002.0564.16929
10028.3364.7237110120.2971.4996110143.2970.1797710202.4169.6472310238.54 66.2752
10254.9666.3706510274.6770.2108810307.5170.8743110356.78 69.724810392.9172.20687
10435.6173.36616 10458.676.4176110494.7374.3903410704.9476.2994210800.1976.36051
10813.3374.9260310846.1776.7874710902.0174.9908810934.8577.7266711001.4977.65026
#Mann= 3 , 0 , 0
9653.729    0.12       09653.729    0.12       011001.49    0.12       0
#XS Ineff= 2 , 0
       0                               0
Bank Sta=9653.729,11001.49
Exp/Cntr=0.3,0.1

Type RM Length L Ch R = 1 ,12745.67,461.563000,461.563000,461.563000
XS GIS Cut Line= 6
1228710.24545598620343.7024618831228313.43145776620317.750476092
1228091.00537482620256.6637294441227839.18535274620214.169724479
1227587.91402176620191.9519835111227014.63068208 620182.00642848
#Sta/Elev= 30
9349.06685.030899402.79884.149449415.94285.977359432.37283.566269494.80583.44877
9524.37980.870149573.66882.087539645.98876.936789688.80976.030249791.23476.93128
9862.02871.325629882.67271.978949914.133 70.03499996.95861.55127 10030.466.11666
 10097.368.9585310266.2166.2721210355.1470.4320910365.0269.18246   1047771.28893
10500.0170.0927810526.2672.13828 10572.272.9407610634.5472.1255710667.35 73.9059
10762.5174.6680910775.6473.4513110808.4576.0206910844.55 74.926611059.3878.40122
#Mann= 3 , 0 , 0
9349.066  0.0852       09349.066  0.0852       011059.38  0.0852       0
#XS Ineff= 2 , 0
       0                               0
Bank Sta=9349.066,11059.38
Exp/Cntr=0.3,0.1

Type RM Length L Ch R = 1 ,12284.11,461.563000,461.563000,461.563000
XS GIS Cut Line= 6
1228701.00891486619888.1043015421228434.07086039619889.569631249
1228111.88018766619917.7557283941227954.38171831619887.346256822
1227685.07764405619850.0123213231226936.29274869619796.119571462
#Sta/Elev= 30
 9349.1182.56073 9426.3479.534439442.747 80.57059485.40577.725189590.42177.46421
9649.57575.494239695.63176.390119735.10874.925129896.93966.991629946.21266.62453
10002.8457.5106910029.8164.0539410046.6566.1414310163.2364.8828510325.4567.00099
10411.2369.1133310434.2571.3735310483.5969.8105710598.7270.8037610611.8869.75005
10671.0972.7274910756.6171.0188210796.0872.1343810845.4276.06824 10881.674.23789
10934.2374.6337610950.6876.5726610957.2674.8752910970.4174.6111811122.8775.50054
#Mann= 3 , 0 , 0
 9349.11  0.0966       0 9349.11  0.0966       011122.87  0.0966       0
#XS Ineff= 2 , 0
       0                               0
Bank Sta=9349.11,11122.87
Exp/Cntr=0.3,0.1

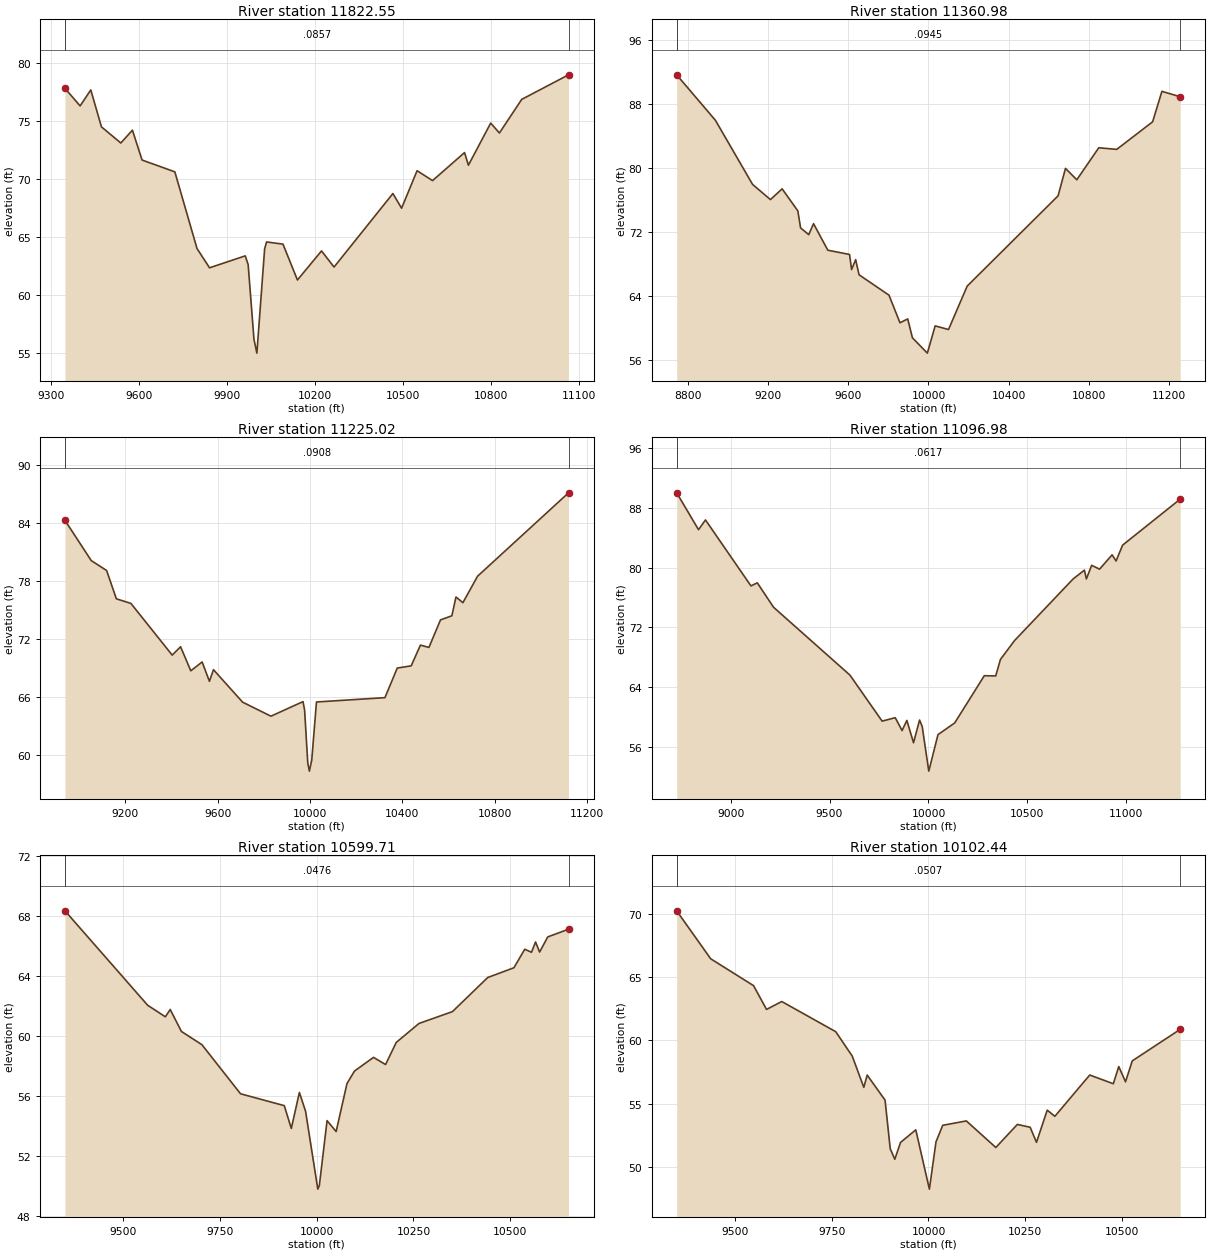
Type RM Length L Ch R = 1 ,11822.55,461.563000,461.563000,461.563000
XS GIS Cut Line= 6
 1228770.1639418619474.8632091131228520.82859921619448.115159109
1228347.09917209619442.7836254841227967.73812768619468.183778703
1227807.51467353619466.4407787321227061.05316111619392.824284792
#Sta/Elev= 30
9349.04277.841769400.64376.330199436.99277.707159473.34274.524819539.34173.13317
9578.84174.240929611.732 71.66559723.377 70.6489 9798.8564.04553 9841.5262.37998
9963.24763.409399973.14662.654579992.94456.2156310002.8555.0297210029.27 64.0137
10035.8564.6076610091.7764.4197610141.0461.3301910223.0863.8366310265.7462.44512
10466.2468.7798310495.8667.51539 10548.670.74576 10601.469.8933310710.3272.30987
10723.5271.2225710799.4374.8499310829.1373.9938910905.0476.8903711064.5379.00755
#Mann= 3 , 0 , 0
9349.042  0.0857       09349.042  0.0857       011064.53  0.0857       0
#XS Ineff= 2 , 0
       0                               0
Bank Sta=9349.042,11064.53
Exp/Cntr=0.3,0.1

Type RM Length L Ch R = 1 ,11360.98,135.960100,135.960100,135.960100
XS GIS Cut Line= 6
1229333.18533704619372.9312284481228803.11683353619210.952378847
1228289.69861278619075.6590340171227852.14697054618926.820738926
1227449.57246718618846.7935900181226902.64245784618768.019098816
#Sta/Elev= 30
8744.48491.685668937.60585.990829122.97677.956319211.99576.055739270.19977.40176
9348.64874.643239362.26272.511529403.10471.660899426.92873.039259498.22469.71224
9606.501 69.18039616.65267.288919636.95468.532269653.87366.635599803.07364.08337
9857.98460.623089896.64861.107469920.03258.739199994.41556.8205410033.3860.23137
10100.03  59.77910193.1665.2199710646.5476.5289310683.2279.9626410739.7478.54084
10849.3182.5467810938.9582.3454411117.8485.8021911164.1689.6173311255.51 88.9378
#Mann= 3 , 0 , 0
8744.484  0.0945       08744.484  0.0945       011255.51  0.0945       0
#XS Ineff= 2 , 0
       0                               0
Bank Sta=8744.484,11255.51
Exp/Cntr=0.3,0.1

Type RM Length L Ch R = 1 ,11225.02,128.039900,128.039900,128.039900
XS GIS Cut Line= 4
1229166.68848112619256.9219120741228253.64054143618913.657705724
 1227931.2858299618816.0800633131227079.22391668618648.804104909
#Sta/Elev= 30
8939.10284.297339052.93280.127949119.52779.098769161.58876.168429224.67875.69087
9403.43570.334569439.69671.202139484.05168.704699533.121 69.62379564.66667.61799
9582.19268.823179708.373  65.4579831.04964.003759970.00165.513629976.85764.62918
9990.56959.162859997.42458.3107310007.7159.4452610028.2765.4766510324.6565.92385
10378.1468.9921510438.3369.2197910478.4571.3692510515.2271.1293210565.3873.98277
10614.5374.4077710632.2576.3580310662.3475.7654210725.8678.5096611119.6787.14964
#Mann= 3 , 0 , 0
8939.102  0.0908       08939.102  0.0908       011119.67  0.0908       0
#XS Ineff= 2 , 0
       0                               0
Bank Sta=8939.102,11119.67
Exp/Cntr=0.3,0.1

Type RM Length L Ch R = 1 ,11096.98,497.272300,497.272300,497.272300
XS GIS Cut Line= 6
1229399.53054113619230.8296126971229064.58501312619099.274085754
1228530.14790643618868.7502848121228329.02125879 618795.09910273
1227566.14922295618609.1670846191226970.80435027 618509.66584756
#Sta/Elev= 30
8727.24790.039678837.68285.09868  8872.886.404519102.68277.557439134.83977.96763
9216.70374.700679602.90665.601529765.83159.423669832.05359.885169866.645 58.1587
9890.70559.521229924.57956.526399955.05559.567219968.36258.7136910001.6252.71959
10048.23 57.615710132.7259.1813110282.2665.5142810340.0465.4873310363.8367.69438
 10435.270.2270510731.3978.4921210788.3179.6707910798.35 78.495410825.0280.31557
10865.0379.8063810928.3881.7239610948.3780.9016910981.5883.0271911272.7989.19924
#Mann= 3 , 0 , 0
8727.247  0.0617       08727.247  0.0617       011272.79  0.0617       0
#XS Ineff= 2 , 0
       0                               0
Bank Sta=8727.247,11272.79
Exp/Cntr=0.3,0.1

Type RM Length L Ch R = 1 ,10599.71,497.272300,497.272300,497.272300
XS GIS Cut Line= 6
1228902.87701099618746.711808815 1228534.1522921 618465.85936106
1228381.15033603618292.0873356611228302.87623691618229.307078418
1228101.81452581618108.3103617861227850.83249935 618009.46707248
#Sta/Elev= 30
9349.06968.362369562.87162.057249608.63361.285329621.14461.773959650.06860.30888
9703.08259.424929802.91756.146089916.03355.352839934.239 53.82869955.11856.23311
 9971.19 54.970810002.7549.7777610006.6750.0098710026.67 54.351310050.1453.62368
10078.1556.8269310097.6757.6636710146.7258.5751810177.9758.0977510205.53  59.574
 10264.360.8401710350.8161.6310310442.0963.90957 10509.864.5612610537.7665.79758
10555.2465.5951210565.7266.2819910576.2165.6089910597.1866.6192610650.9167.13397
#Mann= 3 , 0 , 0
9349.069  0.0476       09349.069  0.0476       010650.91  0.0476       0
#XS Ineff= 2 , 0
       0                               0
Bank Sta=9349.069,10650.91
Exp/Cntr=0.3,0.1

Type RM Length L Ch R = 1 ,10102.44,710.167000,710.167000,710.167000
XS GIS Cut Line= 6
 1229216.4002115618503.6349385231229052.00481918618357.382751572
1228794.33571253618060.0961365451228600.34733348617881.974957897
 1228419.2436633617769.5541859171228219.03844267617704.285341525
#Sta/Elev= 30
9349.08270.235389436.92166.452029547.79764.329779581.40962.450689620.69163.07668
9760.34460.693559802.99458.767059832.84956.301419841.59157.269519887.80355.29347
 9901.1951.45258 9912.9550.626599927.86551.953879967.24552.9475810002.3748.26705
 10019.551.9970910036.8753.3039810097.8853.65135 10174.251.5540510229.8253.37414
10262.9653.1484510279.2851.9619710307.0354.4993710326.8554.0168410416.9457.27535
10477.9356.58521   1049257.9438810509.4656.7377910526.91 58.391110650.9260.88163
#Mann= 3 , 0 , 0
9349.082  0.0507       09349.082  0.0507       010650.92  0.0507       0
#XS Ineff= 2 , 0
       0                               0
Bank Sta=9349.082,10650.92
Exp/Cntr=0.3,0.1

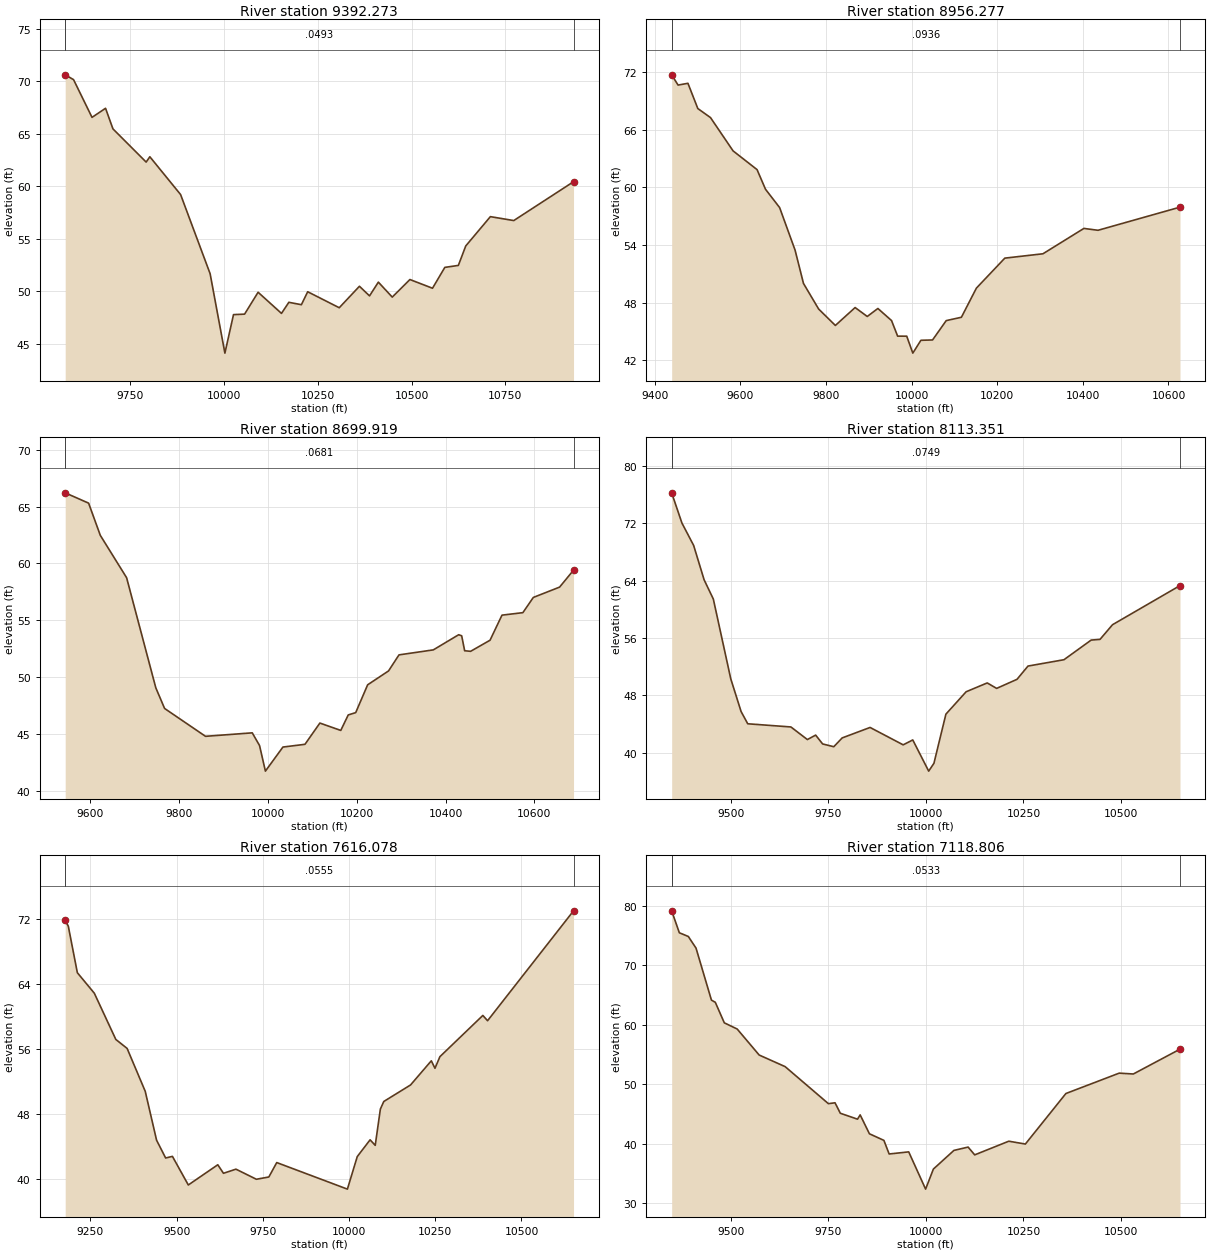
Type RM Length L Ch R = 1 ,9392.273,435.996100,435.996100,435.996100
XS GIS Cut Line= 4
1229541.75438482617631.671486214 1228935.3607524617643.277105972
1228584.41859865617562.8444005551228195.50249267617579.446197316
#Sta/Elev= 30
9576.19970.625149598.50170.164279647.72366.570779683.81967.435189703.50765.47471
9792.10662.30844 9801.9562.816429883.98659.21347 9962.7451.6664310002.1244.09896
10025.0947.7687710054.62 47.814610090.7249.9014310153.0647.8854210172.75 48.9429
10206.16 48.714610222.98 49.949710307.13 48.424810360.9950.4711310387.91 49.5548
10411.4750.86497 10448.549.4383910495.62 51.113710555.8850.2840910588.7252.27091
10624.8452.4597510644.5454.3147710710.2257.1068810772.6156.7342110932.02 60.4358
#Mann= 3 , 0 , 0
9576.199  0.0493       09576.199  0.0493       010932.02  0.0493       0
#XS Ineff= 2 , 0
       0                               0
Bank Sta=9576.199,10932.02
Exp/Cntr=0.3,0.1

Type RM Length L Ch R = 1 ,8956.277,256.357300,256.357300,256.357300
XS GIS Cut Line= 4
1229422.79678228 617181.953720511229158.76893273617205.164960057
1228745.58253145617374.7260909971228272.54706937617422.595078796
#Sta/Elev= 30
9439.83371.733049454.77970.664579477.83470.849039500.88868.21921 9530.5367.27587
9583.22563.806639639.21561.855049658.976 59.80779691.91157.901469728.05953.46208
9747.65649.99144 9783.1247.32247 9822.1345.614799868.23247.479449896.60346.54921
9921.42747.382679953.345 46.1217 9967.5344.500599988.808 44.495110002.9942.72995
10021.8844.06719 10049.144.1029310081.0146.1183110116.4846.46835 10151.549.50483
10217.8652.62955 10306.953.0834410402.5355.72602 10435.555.5315510626.9657.94318
#Mann= 3 , 0 , 0
9439.833  0.0936       09439.833  0.0936       010626.96  0.0936       0
#XS Ineff= 2 , 0
       0                               0
Bank Sta=9439.833,10626.96
Exp/Cntr=0.3,0.1

Type RM Length L Ch R = 1 ,8699.919,586.568700,586.568700,586.568700
XS GIS Cut Line= 3
1229348.93595827617038.480495453 1228821.5922083617079.713134348
1228220.46373606617214.261745468
#Sta/Elev= 30
 9543.0966.213199595.82765.304929622.15462.472089681.38958.745519747.20649.05126
9766.95147.239489859.09544.788169964.40245.093679980.85643.97438 9994.0241.72543
10033.51 43.843710083.1144.0835110116.7345.95449 10163.845.3068810180.6146.66979
10197.4246.8732810224.3149.3205210271.3850.5422510294.9151.9538810372.2452.39376
10429.39  53.72810436.1253.6324410442.8452.3169710456.29 52.2677   1050053.24293
10526.8955.4494810573.9655.6698410597.49 57.008410656.6557.9164610688.0559.40814
#Mann= 3 , 0 , 0
 9543.09  0.0681       0 9543.09  0.0681       010688.05  0.0681       0
#XS Ineff= 2 , 0
       0                               0
Bank Sta=9543.09,10688.05
Exp/Cntr=0.3,0.1

Type RM Length L Ch R = 1 ,8113.351,497.272300,497.272300,497.272300
XS GIS Cut Line= 6
1229295.84742833616555.7567590711229147.94293653616587.560712555
1229020.89779708616626.3638403071228719.95280881616749.779106238
1228476.72591155 616819.576207291228068.42978742616981.078081675
#Sta/Elev= 30
9349.05276.247469375.26272.039519405.33468.909769432.16464.112729455.75561.42936
9500.36850.309679526.83645.741269543.88544.030819654.45943.587219696.62541.82913
9717.80642.452269735.67541.217519764.26640.832469785.70942.057819857.18543.51828
9942.00941.091819966.56141.7777510007.32 37.426610020.7338.5173910051.3945.37226
10103.1848.4980610157.2149.7284810181.3648.9681110233.5250.2326710261.6652.08178
10353.7652.9667610423.4155.7053410446.1455.8054910478.1157.8496110650.9563.30714
#Mann= 3 , 0 , 0
9349.052  0.0749       09349.052  0.0749       010650.95  0.0749       0
#XS Ineff= 2 , 0
       0                               0
Bank Sta=9349.052,10650.95
Exp/Cntr=0.3,0.1

Type RM Length L Ch R = 1 ,7616.078,497.272300,497.272300,497.272300
XS GIS Cut Line= 6
 1229190.5158194616352.7166065721228971.35439569616350.936326876
1228464.76636732616378.5345457051228131.11513597 616531.12280713
1227970.82464728616582.9571652261227765.81995976616634.743133366
#Sta/Elev= 30
9176.72271.772079185.70871.066329211.95665.34557 9261.1762.824649323.508 57.1447
9356.31756.035599408.83350.764239441.69744.756049467.988 42.56849487.706 42.7662
9533.73439.251059619.26641.735399635.71440.68686  9671.941.195449731.11439.95422
9767.26840.232549790.24242.005919995.13138.7408310023.6942.7370110060.9444.80344
10075.8444.1226910090.7448.5781910100.6349.5151410178.2651.5448510238.4954.51599
10249.1253.5964310263.4255.0233310387.9360.0928710401.6559.4445410650.9372.95351
#Mann= 3 , 0 , 0
9176.722  0.0555       09176.722  0.0555       010650.93  0.0555       0
#XS Ineff= 2 , 0
       0                               0
Bank Sta=9176.722,10650.93
Exp/Cntr=0.3,0.1

Type RM Length L Ch R = 1 ,7118.806,497.272200,497.272200,497.272200
XS GIS Cut Line= 6
 1229207.6699992616211.8154473531228951.41565329616186.511659329
1228641.34823299 616115.089213211228452.32835175616091.830099914
1228175.67447424615999.902076631 1227933.4646433615986.287613418
#Sta/Elev= 30
9349.05179.110979368.66775.426279391.67774.80149  9411.472.852689450.89864.11039
9460.78163.747549483.83960.297959516.84159.255119573.10754.888599639.64552.93692
9750.44746.716069767.38946.864439780.94345.105359824.99244.110859831.76944.82894
9855.48841.65859 9892.5740.54719    990638.262029956.096 38.61889999.37632.35972
10019.2935.7291610071.8338.8629110108.2239.4232610125.1138.1143310212.4140.40985
10254.8639.9325310358.6848.4226810495.1751.8437110531.3651.7007410650.8555.87163
#Mann= 3 , 0 , 0
9349.051  0.0533       09349.051  0.0533       010650.85  0.0533       0
#XS Ineff= 2 , 0
       0                               0
Bank Sta=9349.051,10650.85
Exp/Cntr=0.3,0.1

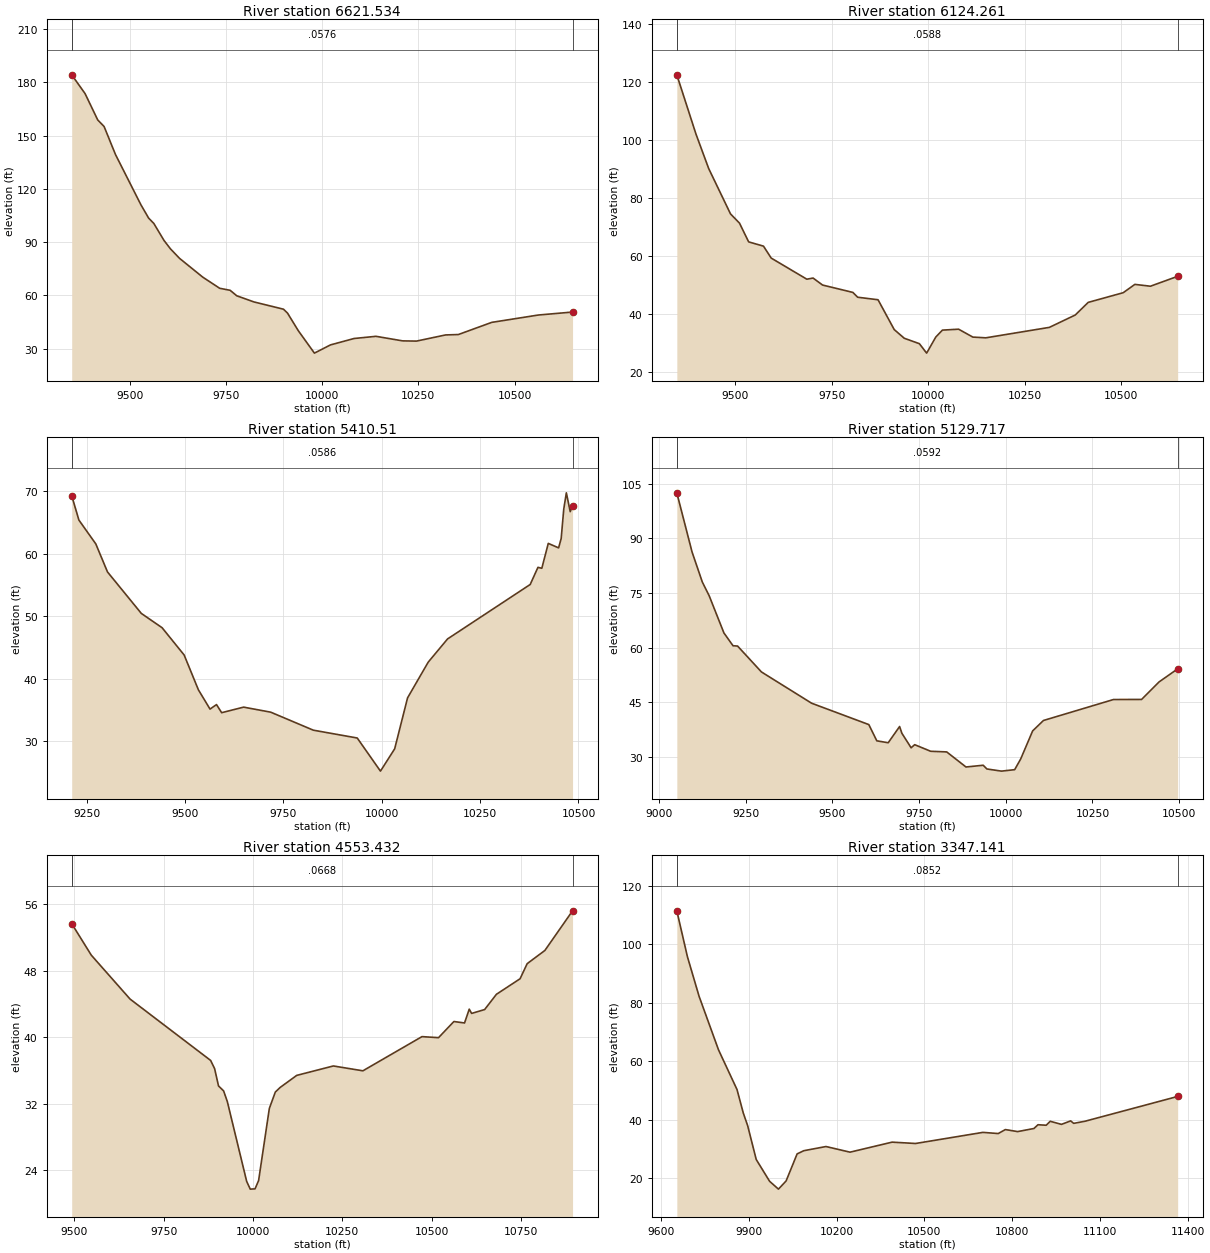
Type RM Length L Ch R = 1 ,6621.534,497.272300,497.272300,497.272300
XS GIS Cut Line= 6
1229380.03986401615878.0070025251229046.54651063615826.764688602
1228705.93917788615714.5132825941228599.16711961615691.932273857
1228402.67429122615701.0277639931228110.69433411615764.785867253
#Sta/Elev= 30
9349.039184.15489383.711173.61889416.715158.75359433.216155.08469462.919139.2772
9529.192110.9307 9549.12103.50849562.438100.54529589.07490.937449605.72886.24353
9629.20680.919339689.60770.335549733.66764.056769760.88862.915869778.04559.83576
9822.71256.377239899.566 52.28159910.04650.073569937.99340.204169979.91327.57035
 10021.532.18406   1008335.79898 10139.937.0285410209.0334.4660310245.1334.33388
10320.9237.8033610354.0238.0282910440.8444.8728410562.0549.0079410650.9150.68422
#Mann= 3 , 0 , 0
9349.039  0.0576       09349.039  0.0576       010650.91  0.0576       0
#XS Ineff= 2 , 0
       0                               0
Bank Sta=9349.039,10650.91
Exp/Cntr=0.3,0.1

Type RM Length L Ch R = 1 ,6124.261,713.751700,713.751700,713.751700
XS GIS Cut Line= 6
1229155.59412788615141.9657418431228986.73137093615161.568588966
1228855.19685196615211.5909862181228655.96242616615437.030528262
1228569.53679761615496.7934782051228006.91117153615618.096457854
#Sta/Elev= 30
9349.239122.60759398.843102.1585 9431.7890.259329488.23574.620119511.55671.42364
 9535.2664.95292 9573.6163.489869593.67559.359179685.89252.078829702.10952.47073
9726.62250.058639805.04147.520759817.62345.850749870.30144.983669912.20934.69131
9938.20231.694169977.33229.823489996.14126.5627810019.8432.1149710036.9934.50212
10078.9434.8236110115.8632.0935610149.4231.8457310313.8835.44666   1038139.71712
10414.5644.0764110505.1847.4147110535.3950.2866910575.66  49.65610646.2253.06941
#Mann= 3 , 0 , 0
9349.239  0.0588       09349.239  0.0588       010646.22  0.0588       0
#XS Ineff= 2 , 0
       0                               0
Bank Sta=9349.239,10646.22
Exp/Cntr=0.3,0.1

Type RM Length L Ch R = 1 , 5410.51,280.792900,280.792900,280.792900
XS GIS Cut Line= 4
1228996.29025608615104.5477834641228703.24835715615139.364642754
1228282.54464084615150.9702625131227725.47489235615159.674477324
#Sta/Elev= 30
9211.83469.310619230.13365.397969273.08461.587239302.81957.098529388.72150.46777
9441.58348.17527 9497.7543.801779533.91338.233579563.45235.152189579.86335.87656
9592.991 34.57699648.786 35.4676 9717.7134.661749826.01931.779539937.60730.52834
9996.66925.2283110032.7628.7947110065.5736.9555710118.07 42.668710167.2946.38408
10377.2955.0943610396.9857.8347110406.8257.6892810423.2361.6680810449.4860.95407
10456.04  62.457 10462.667.1602610469.1769.7600210479.0166.7486610484.9467.66181
#Mann= 3 , 0 , 0
9211.834  0.0586       09211.834  0.0586       010484.94  0.0586       0
#XS Ineff= 2 , 0
       0                               0
Bank Sta=9211.834,10484.94
Exp/Cntr=0.3,0.1

Type RM Length L Ch R = 1 ,5129.717,576.285300,576.285300,576.285300
XS GIS Cut Line= 6
 1229133.3771131614999.4342786521228902.10295402614990.254296591
1228467.86462358615017.013011349 1228258.3979763614904.740820188
1227986.80148295 614816.503269921227741.26979923614758.312118483
#Sta/Elev= 30
 9051.28102.55669095.10586.32236 9124.7178.056619144.42674.29066 9187.11 64.0298
9213.37460.505159226.49760.424819295.40953.297269440.13444.699259605.00238.83038
9628.02834.365669660.92233.837959693.75438.298639700.36836.441089727.02732.44163
9737.19733.30378 9783.4531.491279829.59231.316059885.16327.16953 9934.8327.64887
9945.60326.623029987.53226.0324210025.5826.4326210042.8929.35628 10077.537.09605
10108.6539.9580910310.67 45.721510391.6845.7422210442.0750.56373 10495.754.15182
#Mann= 3 , 0 , 0
 9051.28  0.0592       0 9051.28  0.0592       0 10495.7  0.0592       0
#XS Ineff= 2 , 0
       0                               0
Bank Sta=9051.28,10495.7
Exp/Cntr=0.3,0.1

Type RM Length L Ch R = 1 ,4553.432,1206.290300,1206.290300,1206.290300
XS GIS Cut Line= 6
1228910.07518802 614857.285168461228816.54399564614794.632405122
 1228612.3319902614606.4233340711228538.62610205614579.547772727
1228397.13597591614552.4408154911227615.22150466 614654.83001779
#Sta/Elev= 30
9492.48853.671369547.34449.87125 9655.97 44.57999881.43337.19362 9892.5736.20995
9903.52634.11989 9917.8533.517949928.285 32.2223 9982.36 22.62399992.38921.68892
10005.7721.7206210015.7822.7169410045.8431.4070910062.5333.3778110075.8933.93028
10122.4935.3889810225.0736.5250710307.7935.9409910473.2340.0591810519.5539.93293
10562.5741.8792810592.3541.7026210605.5843.36631 10612.242.85523 10648.643.31902
10681.69 45.158810747.8647.0298910767.7248.8470610817.35 50.440210894.8155.21278
#Mann= 3 , 0 , 0
9492.488  0.0668       09492.488  0.0668       010894.81  0.0668       0
#XS Ineff= 2 , 0
       0                               0
Bank Sta=9492.488,10894.81
Exp/Cntr=0.3,0.1

Type RM Length L Ch R = 1 ,3347.141,377.414900,377.414900,377.414900
XS GIS Cut Line= 5
1229187.78298211614068.7462198881228975.98042148 614036.83076556
 1228735.1638115614170.2953927811228590.09356448614164.492582902
1227577.50324044614524.266795471
#Sta/Elev= 30
9654.922111.39149691.10695.71051 9730.92 82.17669797.27863.874299860.31750.32757
9881.67542.324959896.67937.973339925.917 26.41639971.69918.9543310001.7116.29207
10027.9619.0959310065.4728.3285610088.3529.4234210163.9730.8485910246.0628.92117
10389.6632.3457210469.7431.8879110699.5435.6833310751.7635.2845610776.1436.64132
10817.9235.9514710873.6337.0057910887.5538.2952110915.41 38.122110929.3339.47113
10967.6338.4204610998.9739.6034411009.4138.7669311047.7139.4833511364.2347.96004
#Mann= 3 , 0 , 0
9654.922  0.0852       09654.922  0.0852       011364.23  0.0852       0
#XS Ineff= 2 , 0
       0                               0
Bank Sta=9654.922,11364.23
Exp/Cntr=0.3,0.1

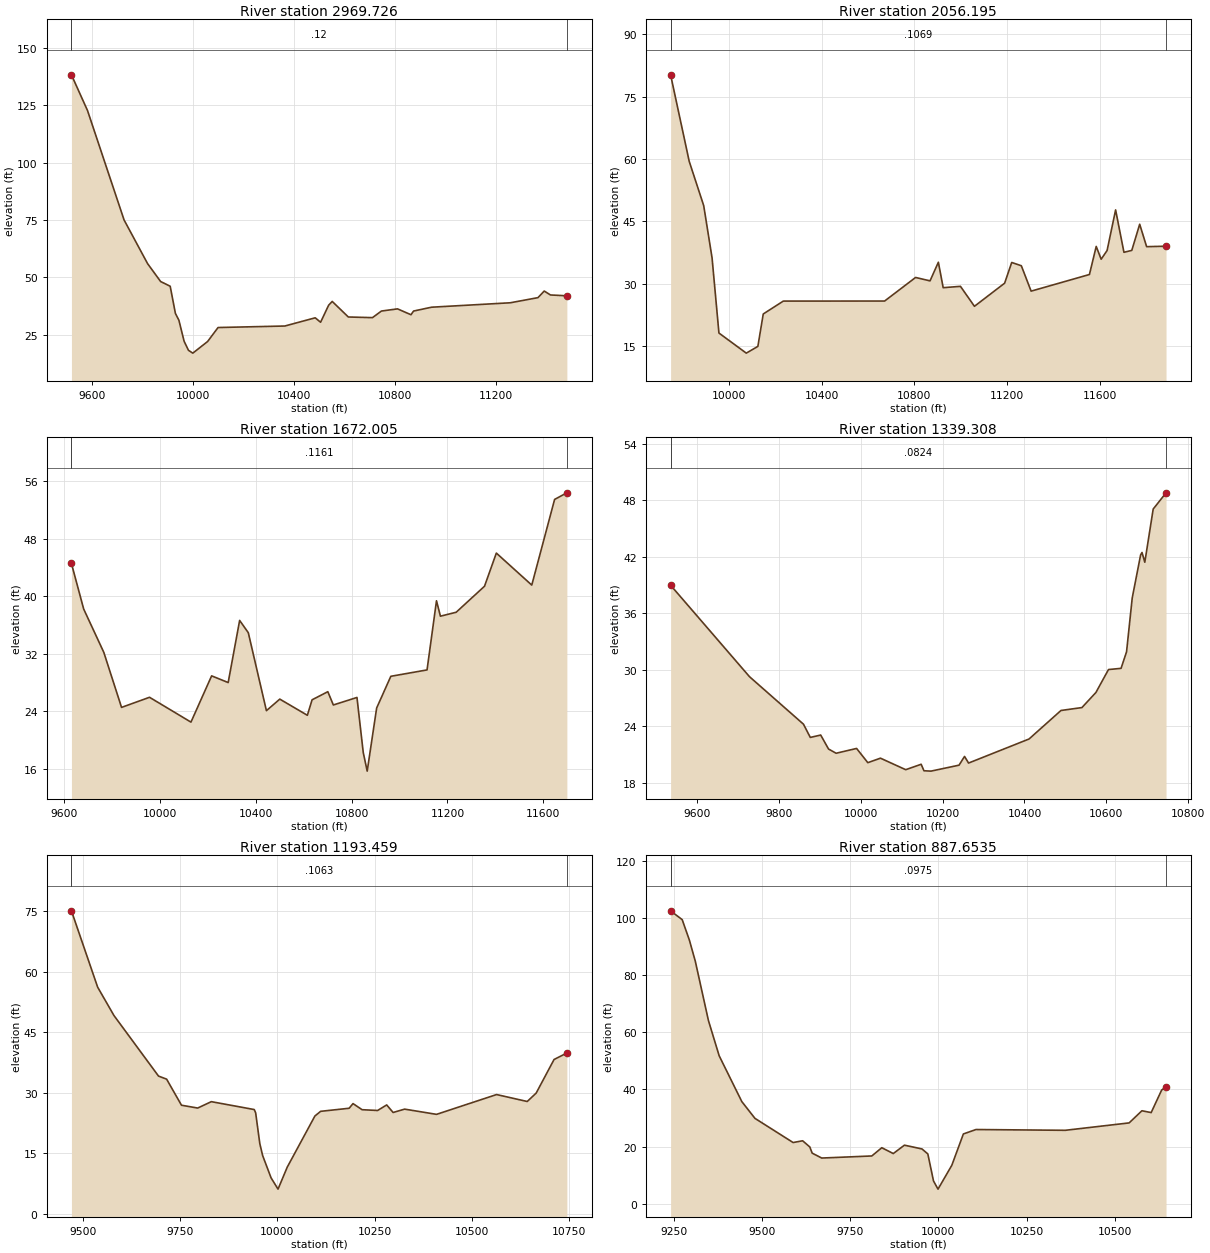
Type RM Length L Ch R = 1 ,2969.726,913.530900,913.530900,913.530900
XS GIS Cut Line= 3
1229324.14901429613639.3382887841228604.60058916613871.450683966
1227487.55968729614326.971259549
#Sta/Elev= 30
9519.411 138.2779583.084122.71929727.87175.038369820.94856.019489872.65848.21292
9910.57846.147389931.26234.292429945.05131.345929965.73522.175939982.97218.23168
10000.2117.0035310058.8122.0642510100.1828.1596810364.5928.8158210485.0532.39377
10506.3130.45851 10538.237.8836910552.3739.5290510616.1532.7482210711.8132.46865
10747.2535.3392110811.0236.2888710864.1733.74412 10874.835.3434810945.6637.01216
11257.4638.9414911367.2941.18024 11392.144.05449 11416.942.3469711481.8241.99089
#Mann= 3 , 0 , 0
9519.411    0.12       09519.411    0.12       011481.82    0.12       0
#XS Ineff= 2 , 0
       0                               0
Bank Sta=9519.411,11481.82
Exp/Cntr=0.3,0.1

Type RM Length L Ch R = 1 ,2056.195,384.190200,384.190200,384.190200
XS GIS Cut Line= 6
1229297.65455595613397.9543233511229107.74439421613384.106083289
 1229016.9120234613410.9328138831228706.14976206613355.000604644
 1228239.9310987 613443.976981671227420.82737365614118.070103884
#Sta/Elev= 30
9747.84680.213549828.16459.39846 9890.72 48.75289926.84536.156879956.41718.10566
10074.4813.2738910124.4114.8919310147.7222.6902510234.2825.7891410671.4525.80311
10805.0531.4724310867.4430.6531210903.4135.1382710924.1729.0148110998.7229.33779
11059.0724.5373411189.2930.0934311219.92 35.077611261.4334.2918511303.6428.18336
 11555.332.1834811584.6138.9397511605.9335.8598411631.5137.95832 11668.347.72129
11704.2537.5254811738.1137.9842611772.2244.2754611802.0738.8822311885.9238.98898
#Mann= 3 , 0 , 0
9747.846  0.1069       09747.846  0.1069       011885.92  0.1069       0
#XS Ineff= 2 , 0
       0                10522.73       0
Bank Sta=9747.846,11885.92
Exp/Cntr=0.3,0.1

Type RM Length L Ch R = 1 ,1672.005,332.697300,332.697300,332.697300
XS GIS Cut Line= 5
1229401.92029765613076.4237400741229130.09686527613013.695255667
1228947.13878569613088.6209453641228741.57034326 613156.62855038
1227368.60208476613056.155895829
#Sta/Elev= 30
9629.28244.550679680.377 38.20899764.55432.170789838.62924.509149955.48425.91683
10128.6222.4601210215.0128.8999910284.1227.9680910332.0236.6163410368.2134.90759
10443.87 24.052510499.7925.6625110614.9323.4116410634.6625.5660910700.46 26.6957
10723.4824.8469410822.17 25.893810848.4918.2107910864.9415.6382810904.41  24.423
10963.6228.8379611114.95  29.72711154.4239.3535211170.87 37.206211236.6637.75437
11355.0941.3783311404.4345.9909811552.4641.5344711647.8653.4606911699.12  54.379
#Mann= 3 , 0 , 0
9629.282  0.1161       09629.282  0.1161       011699.12  0.1161       0
#XS Ineff= 2 , 0
       0                10345.63       0
Bank Sta=9629.282,11699.12
Exp/Cntr=0.3,0.1

Type RM Length L Ch R = 1 ,1339.308,145.849400,145.849400,145.849400
XS GIS Cut Line= 5
1229486.39830935612966.3132250761229106.18997604612764.924336165
 1228837.0927538612683.3271139561228660.00942045612676.382669508
1228350.83628362612587.618303701
#Sta/Elev= 30
9535.47838.964359728.254 29.25059860.09724.20695 9876.7622.800989902.15223.05502
9921.312 21.56949939.875 21.12189989.852 21.631710017.2820.1205210048.1320.59854
10109.8419.3751210147.56 19.950710154.4119.2616110171.55 19.222810240.1219.85516
10253.54  20.78410263.39 20.079710411.1422.6353510489.1425.6632810540.3425.97246
10574.4727.5735810605.1930.0090810635.9130.1382410649.3531.8951210663.2237.62026
 10683.742.1843310687.1142.4421310693.9441.4085910714.4247.0558110745.8148.77801
#Mann= 3 , 0 , 0
9535.478  0.0824       09535.478  0.0824       010745.81  0.0824       0
#XS Ineff= 2 , 0
       09939.181        10246.89       0
Bank Sta=9535.478,10745.81
Exp/Cntr=0.3,0.1

Type RM Length L Ch R = 1 ,1193.459,305.805100,305.805100,305.805100
XS GIS Cut Line= 6
1229602.47309184612804.2834970941229209.24791891612662.159507292
1229089.45668409612607.6006230961229032.00152677612557.140833121
1228840.56497604612523.6048917171228387.43997604 612499.29933618
#Sta/Elev= 30
9470.09275.121379537.52256.203139579.43449.177249694.11534.156639714.96633.39599
9753.19226.933569794.89426.234579829.96427.816019940.33125.861799943.93525.08414
9954.74817.388189961.95714.464549983.5838.95040910001.566.13581710025.3111.59358
10096.4724.26962 10111.2 25.420210184.4826.1817710194.4727.3361710217.7925.82304
10257.76 25.631410281.0827.0055110297.6425.1329510327.2125.9656610409.3424.67004
10563.7729.5791310642.6227.8582410665.6229.9412110711.6138.26869 10744.639.87015
#Mann= 3 , 0 , 0
9470.092  0.1063       09470.092  0.1063       0 10744.6  0.1063       0
#XS Ineff= 2 , 0
       0                10218.82       0
Bank Sta=9470.092,10744.6
Exp/Cntr=0.3,0.1

Type RM Length L Ch R = 1 ,887.6535,305.805000,305.805000,305.805000
XS GIS Cut Line= 6
1229712.09275377 612468.049336181229075.04621983612311.760225832
1228928.14866262612419.9124454441228896.94582661612439.091199949
1228874.75785434612448.9270662841228371.81497604612415.966002852
#Sta/Elev= 30
9241.548102.51299274.36999.424649294.638 92.31219311.52884.871179348.68864.12131
9379.09151.777589443.27535.737789480.43529.871949588.53521.40936 9615.5622.02265
9635.82819.860199642.58517.69355 9669.6115.979789811.49116.705879839.72219.59541
9872.29717.551369903.88320.484729953.61319.16244 9970.1917.406889986.2147.962274
    99995.09931210038.0813.4413410070.83 24.407610106.4725.9607810359.4925.68852
10540.3328.2775510576.4932.53015 10602.831.8925810632.3939.7641310644.8940.94438
#Mann= 3 , 0 , 0
9241.548  0.0975       09241.548  0.0975       010644.89  0.0975       0
#XS Ineff= 2 , 0
       09927.265         10103.3       0
Bank Sta=9241.548,10644.89
Exp/Cntr=0.3,0.1

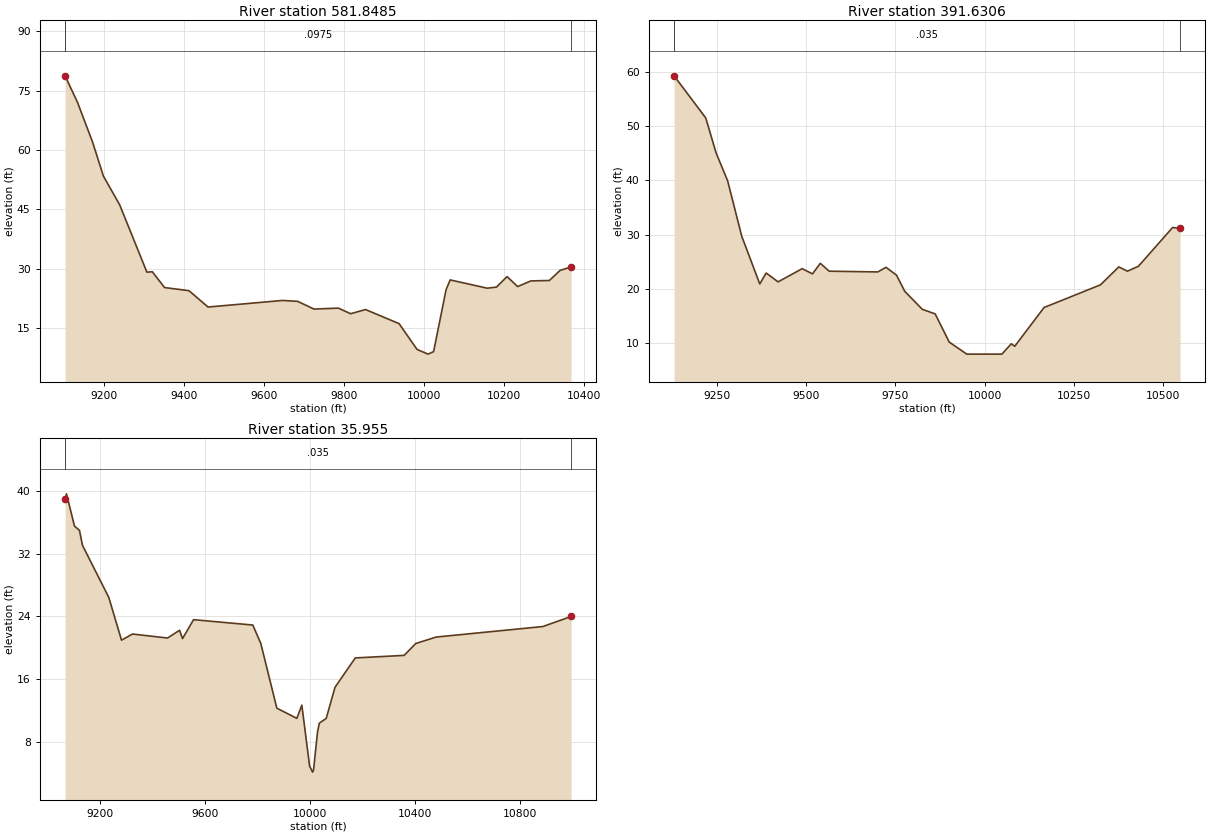
Type RM Length L Ch R = 1 ,581.8485,190.217900,190.217900,190.217900
XS GIS Cut Line= 6
1229726.84797451612349.2581157091229009.13044193612158.143373683
1228971.19035533612153.1935116951228922.29391095612141.279672384
1228802.41206411 612101.408806191228497.77828199612139.669025734
#Sta/Elev= 30
9102.42578.715399133.70571.951569171.052 62.00119198.21353.388869238.95546.11976
9306.85829.127489320.43929.225099350.99525.238869412.10824.44319 9459.64 20.3173
9646.37421.98125 9683.7221.745299724.46219.804269785.575 20.03749816.13118.62427
9853.266 19.68059937.13716.124989981.9859.615636 10009.6 8.4200410023.489.059111
10054.6924.7085210064.8627.1664410157.4525.0742610180.5925.3519410207.0527.99741
 10233.525.4826910266.5626.9124910312.8627.0218810339.3129.5534810367.1130.44586
#Mann= 3 , 0 , 0
9102.425  0.0975       09102.425  0.0975       010367.11  0.0975       0
#XS Ineff= 2 , 0
       09810.587        10078.59       0
Bank Sta=9102.425,10367.11
Exp/Cntr=0.3,0.1

Type RM Length L Ch R = 1 ,391.6306,355.675600,355.675600,355.675600
XS GIS Cut Line= 5
1229810.12239006612236.7251217511229297.73024353612002.604555324
1228990.58063737 611992.660067291228756.80722663611999.312934533
1228456.17252758612091.478316709
#Sta/Elev= 30
9129.34459.281069218.06151.52549 9247.2445.056059279.38239.95645 9319.0629.72106
9369.55920.932379387.59422.947139420.91721.315269488.593 23.74639517.44922.78473
9539.33324.731179564.34123.283299700.62623.146469723.60424.001489753.147 22.5441
9776.12519.573049825.36316.260869861.47115.408369900.86210.21878  9950.1       8
10048.57       810074.839.90240310084.679.45028710166.7316.5863710324.9620.76579
10376.4324.0746510400.4523.2844910431.3324.1873810527.4231.3433610548.3131.15443
#Mann= 3 , 0 , 0
9129.344   0.035       09129.344   0.035       010548.31   0.035       0
#XS Ineff= 2 , 0
       09829.027        10141.68       0
Bank Sta=9129.344,10548.31
Exp/Cntr=0.3,0.1

Type RM Length L Ch R = 1 ,  35.955,0.000000,0.000000,0.000000
XS GIS Cut Line= 6
1229940.66066304612137.6960870621229476.80799422611864.082626566
1229380.84152323611813.8785486671229235.51825616611727.926082075
1229020.31101364611617.3601907491228178.39397749611403.980966389
#Sta/Elev= 30
9067.71238.891029072.98139.607369103.45435.508539122.499 34.95119133.92733.05245
9233.99226.433339282.48120.988199324.397 21.76749457.69921.260259503.408 22.2447
9514.83521.185579556.73523.592959782.21422.910489812.70820.571749873.69612.33671
9949.83311.035549968.95612.716689998.4874.96287410009.684.196029 10013.44.447952
 10028.69.29761710035.5910.43229 10061.711.0281210095.1414.98421 10172.318.72658
10358.4519.0510910402.45 20.5607 10480.321.3821410886.4422.7222510993.9223.99837
#Mann= 3 , 0 , 0
9067.712   0.035       09067.712   0.035       010993.92   0.035       0
#XS Ineff= 2 , 0
       09712.382        10125.47       0
Bank Sta=9067.712,10993.92
Exp/Cntr=0.3,0.1